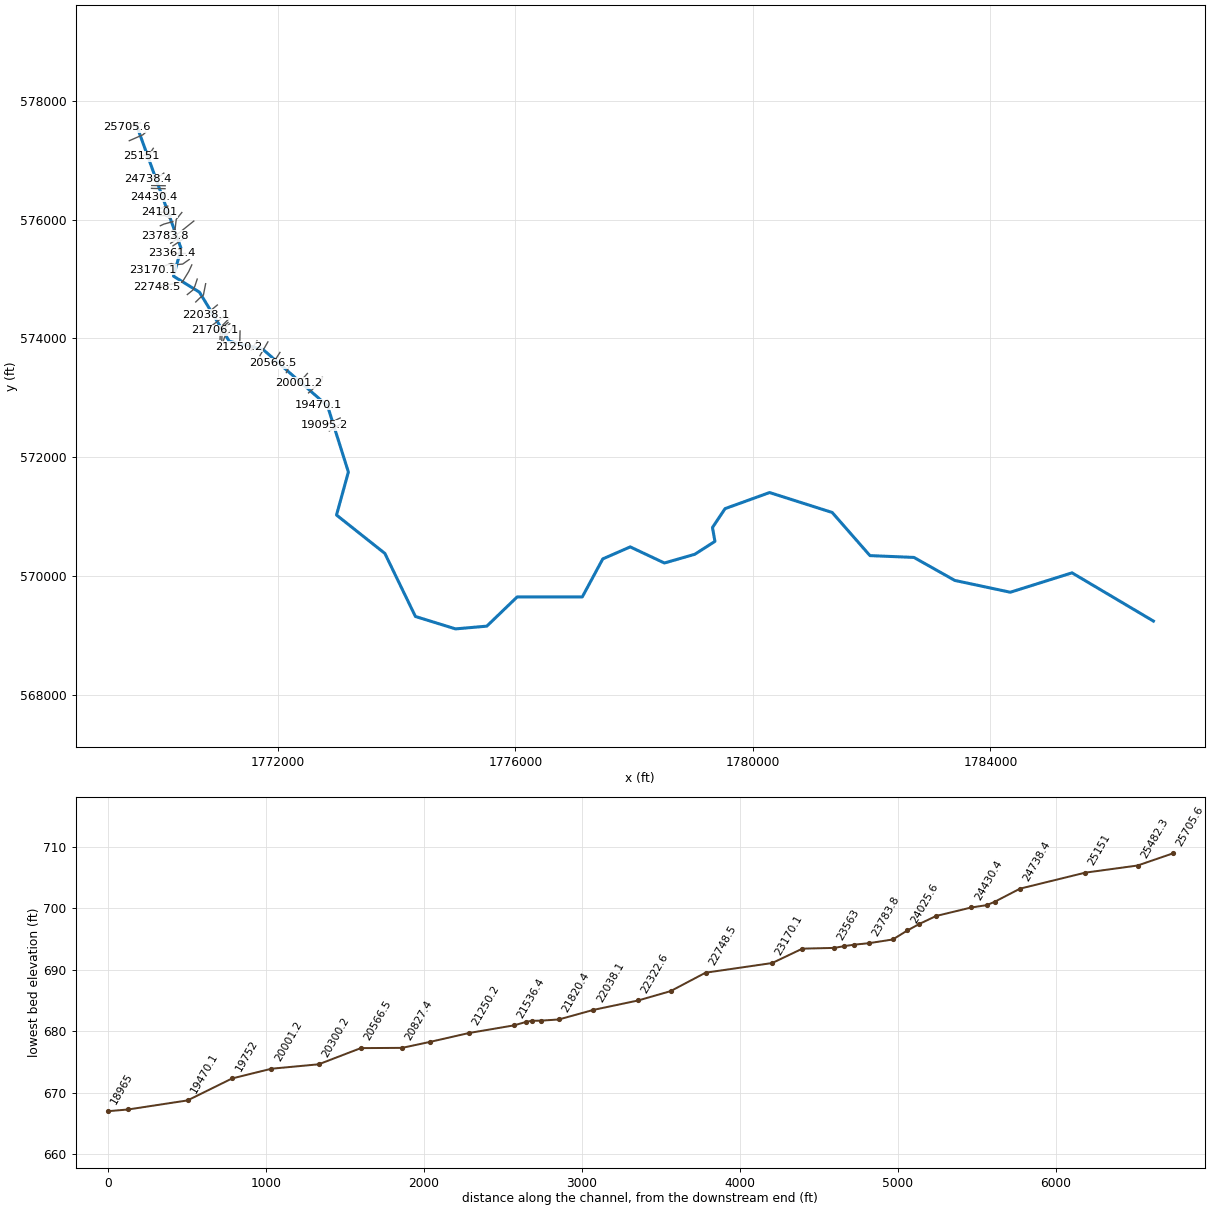
--- ALLENFK.prj (project) ---

Proj Title=ALLENFK
Current Plan=p01
Default Exp/Contr=0,0
English Units
Geom File=g01
Flow File=f01
Plan File=p01
BEGIN DESCRIPTION:
END DESCRIPTION:
DSS Export Rating Curves= 0
DSS Export Rating Curve Sorted= 0
DSS Export Volume Flow Curves= 0
DXF OffsetX= 0
DXF OffsetY= 0
DXF ScaleX= 0
DXF ScaleY= 0

--- ALLENFK.p01 (plan) ---

Plan Title=Floodplain
Program Version=4.00
Geom File=g01
Flow File=f01
K Sum by GR=0
Std Step Tol=0.01
Critical Tol=0.01
Num of Std Step Trials=20
Max Error Tol=0.3
Flow Tol Ratio=0.001
Split Flow NTrial=30
Split Flow Tol=0.02
Split Flow Ratio=0.02
Log Output Level=0
Friction Slope Method=1
Unsteady Friction Slope Method=2
Unsteady Bridges Friction Slope Method=1
Global Log Level=0
CheckData=False
Run HTab=0
Run UNet=0
Run PostProcess=0
UNET Theta=0
UNET Theta Warmup=0
UNET ZTol=0
UNET ZSATol=0
UNET MxIter=0
UNET MaxInSteps=0
UNET DtIC=0
UNET DtMin=0
UNET MaxCRTS=0
UNET WFStab=0
UNET SFStab=0
UNET WFX=0
UNET SFX=0
UNET DSS MLevel=0
UNET DZMax Abort=0
UNET Convert EG Bridges=0
UNET Use Existing IB Tables=0
UNET Froude Limit=0
UNET Froude Power=0
Write IC File=0
Echo Input=False
Echo Output=False
Write Detailed=0

--- ALLENFK.f01 (steady flow) ---

Flow Title=NFF Regression Equation
Program Version=4.10
Number of Profiles= 1
Profile Names=P100yr
River Rch & RM=ALLENFK,Main            ,25705.6
922.2527
River Rch & RM=ALLENFK,Main            ,23688.1
1011.579
River Rch & RM=ALLENFK,Main            ,20827.4
1145.688
River Rch & RM=ALLENFK,Main            ,19470.1
1232.918
River Rch & RM=ALLENFK,Main            ,17316.2
1443.921
River Rch & RM=ALLENFK,Main            ,14853.4
1566.921
River Rch & RM=ALLENFK,Main            ,10544.9
1727.239
River Rch & RM=ALLENFK,Main            ,7081.2
2277.628
River Rch & RM=ALLENFK,Main            ,427.9
2473.499
Boundary for River Rch & Prof#=ALLENFK,Main            , 1
Up Type= 0
Dn Type= 3
Dn Slope=0.006
DSS Import GetInterval= 0
DSS Import GetPeak= 0
DSS Import FillOption= 0

--- ALLENFK.g01 (geometry) ---

Geom Title=USGS 10m DEM
Program Version=4.10

River Reach=ALLENFK         ,Main
Reach XY= 30
     1769611.908      577610.088     1770371.457      575511.129
      1770242.55      575047.588     1770679.586      574778.512
     1771181.353      573952.536     1771751.665      573813.213
     1772836.531      572864.623     1773187.553      571752.263
     1772987.776      571028.056     1773802.012      570382.223
     1774316.624       569321.04     1774992.238       569112.01
     1775519.026      569158.265     1776029.443      569649.584
     1777126.665      569649.584     1777472.151      570290.209
     1777934.516      570491.828     1778510.345      570220.765
     1779021.233      570367.541     1779360.817      570584.902
     1779319.373      570817.987     1779531.179      571135.695
     1780281.179      571406.529      1781336.04      571071.112
     1781971.891      570345.201     1782711.908      570314.819
     1783400.927      569927.449     1784335.172      569728.881
     1785374.668      570055.487     1786746.225      569243.279

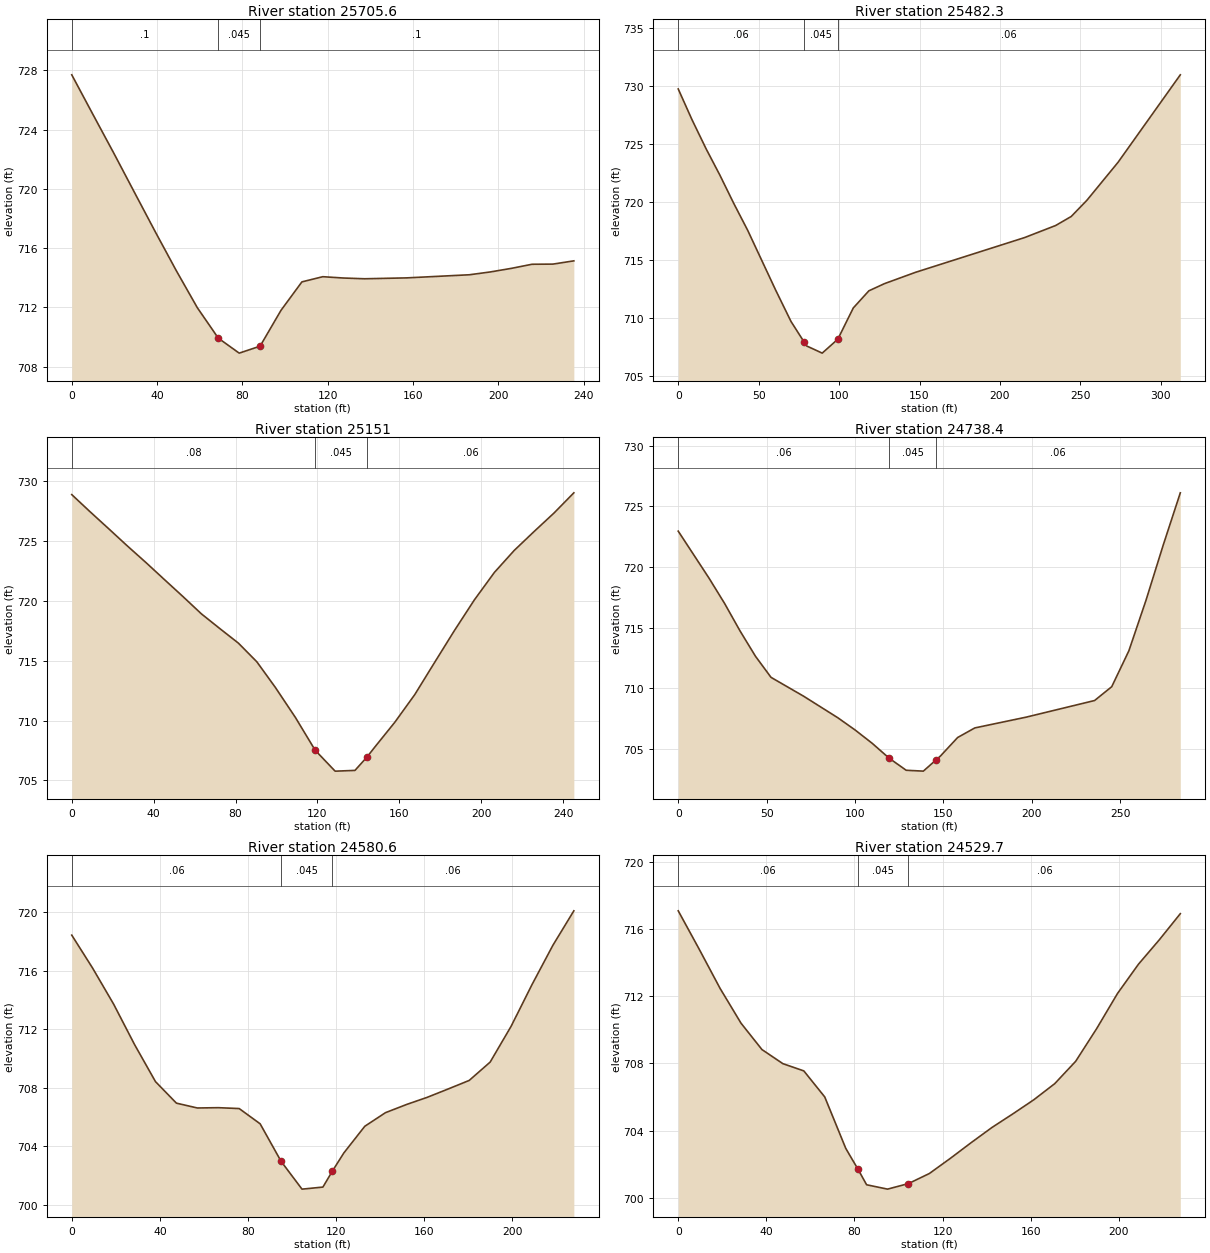
Type RM Length L Ch R = 1 ,25705.6 ,221.5,223.2,224.9
XS GIS Cut Line= 2
     1769683.299      577628.623     1769461.077      577550.845
#Sta/Elev= 27
       0   727.7     9.8  725.06    19.6  722.44    29.4  719.76    39.2  717.09
      49  714.48    58.9  711.97    65.8  710.53    68.7  709.92    78.5  708.91
    80.8  709.02    88.3  709.38    98.1   711.8   107.9  713.72   117.7  714.07
   127.5  713.98   137.3  713.93   147.2  713.96     157  713.99   166.8  714.06
   176.6  714.13   186.4   714.2   196.2  714.39     206  714.63   215.8  714.91
   225.6  714.92   235.4  715.14
#Mann= 3 , 0 , 0
       0      .1       0    68.7    .045       0    88.3      .1       0
Bank Sta=68.7,88.3
XS Rating Curve= 0 ,0
Exp/Cntr=0.3,0.1

Type RM Length L Ch R = 1 ,25482.3 ,332.8,331.3,329.8
XS GIS Cut Line= 3
     1769772.883      577468.901     1769728.438      577427.928
     1769497.848      577327.222
#Sta/Elev= 22
       0  729.71     8.6  727.05    17.3  724.56    25.9  722.28    34.5  719.85
    43.2  717.52    60.4  712.42    70.1  709.67    78.1  707.93    79.8  707.56
    89.5  706.94    99.2  708.14   108.8  710.83   118.5  712.31   128.2  712.93
   147.6  713.91   215.3   716.9   234.6  717.94   244.3  718.72     254  720.11
   273.4  723.39   312.1  730.93
#Mann= 3 , 0 , 0
       0     .06       0    78.1    .045       0    99.2     .06       0
Bank Sta=78.1,99.2
XS Rating Curve= 0 ,0
Exp/Cntr=0.3,0.1

Type RM Length L Ch R = 1 ,25151   ,413.7,412.6,411.2
XS GIS Cut Line= 3
     1769902.223       577199.63     1769846.667      577117.164
     1769709.515      577067.685
#Sta/Elev= 30
       0  728.88       9  727.44    18.1  726.02    27.1   724.6    36.2  723.21
    45.2  721.79    54.2  720.38    63.3  718.92    72.3  717.69    81.4  716.47
    90.4  714.91    99.4  712.78   109.2  710.27   114.2  708.85   118.9  707.52
   128.6  705.78   129.2  705.78   138.3  705.84  144.15  706.95     148  707.79
   157.8  709.87   167.5  712.17   177.2  714.86   186.9  717.53   196.6  720.08
   206.4  722.38   216.1  724.22   225.8   725.8   235.5  727.34   245.2  729.03
#Mann= 3 , 0 , 0
       0     .08       0   118.9    .045       0  144.15     .06       0
Bank Sta=118.9,144.15
XS Rating Curve= 0 ,0
Exp/Cntr=0.3,0.1

Type RM Length L Ch R = 1 ,24738.4 ,164.9,157.8,150.6
XS GIS Cut Line= 3
     1770079.306      576781.661     1770031.129      576743.901
     1769817.587      576680.098
#Sta/Elev= 24
       0  722.96    17.5  719.07    26.2  717.01      35  714.73    43.7  712.65
    52.5  710.91    70.9  709.36    90.3  707.58     100  706.58   109.7  705.48
   119.4  704.24     129  703.25   138.7  703.18     146  704.12   148.4  704.43
   158.1  705.95   167.8  706.74   196.9  707.63   235.6     709   245.3  710.14
     255   713.1   264.7  717.27   274.4   721.8   284.1  726.12
#Mann= 3 , 0 , 0
       0     .06       0   119.4    .045       0     146     .06       0
Bank Sta=119.4,146
XS Rating Curve= 0 ,0
Exp/Cntr=0.3,0.1

Type RM Length L Ch R = 1 ,24580.6 ,50.9,50.9,50.9
XS GIS Cut Line= 2
     1770102.744      576569.421     1769874.879       576574.63
#Sta/Elev= 28
       0  718.42     9.5  716.16      19  713.71    28.5  710.95      38  708.42
    47.5  706.95      57  706.62    66.5  706.64      76  706.58    85.5  705.54
      91  704.06      95  702.98   104.5  701.08     106   701.1     114  701.22
  118.25   702.3   123.5  703.55     133  705.37   142.4   706.3     152  706.86
   161.4  707.35   170.9  707.92   180.4   708.5   189.9  709.75   199.4  712.19
   208.9  715.04   218.4  717.73   227.9  720.08
#Mann= 3 , 0 , 0
       0     .06       0      95    .045       0  118.25     .06       0
Bank Sta=95,118.25
XS Rating Curve= 0 ,0
Exp/Cntr=0.3,0.1

Type RM Length L Ch R = 1 ,24529.7 ,91.5,99.3,107
XS GIS Cut Line= 2
      1770100.14      576519.942     1769872.275      576525.151
#Sta/Elev= 28
       0  717.08     9.5   714.8      19  712.46    28.5  710.39      38  708.82
    47.5  707.98      57  707.55    66.5     706      76  702.95    77.8  702.54
   81.49  701.72    85.5  700.77    92.8  700.57      95  700.51   104.5  700.84
     114  701.44   123.5  702.34     133  703.28   142.4  704.18     152     705
   161.4  705.83   170.9  706.79   180.4  708.12   189.9  710.06   199.4  712.16
   208.9   713.9   218.4  715.36   227.9  716.91
#Mann= 3 , 0 , 0
       0     .06       0   81.49    .045       0   104.5     .06       0
Bank Sta=81.49,104.5
XS Rating Curve= 0 ,0
Exp/Cntr=0.3,0.1

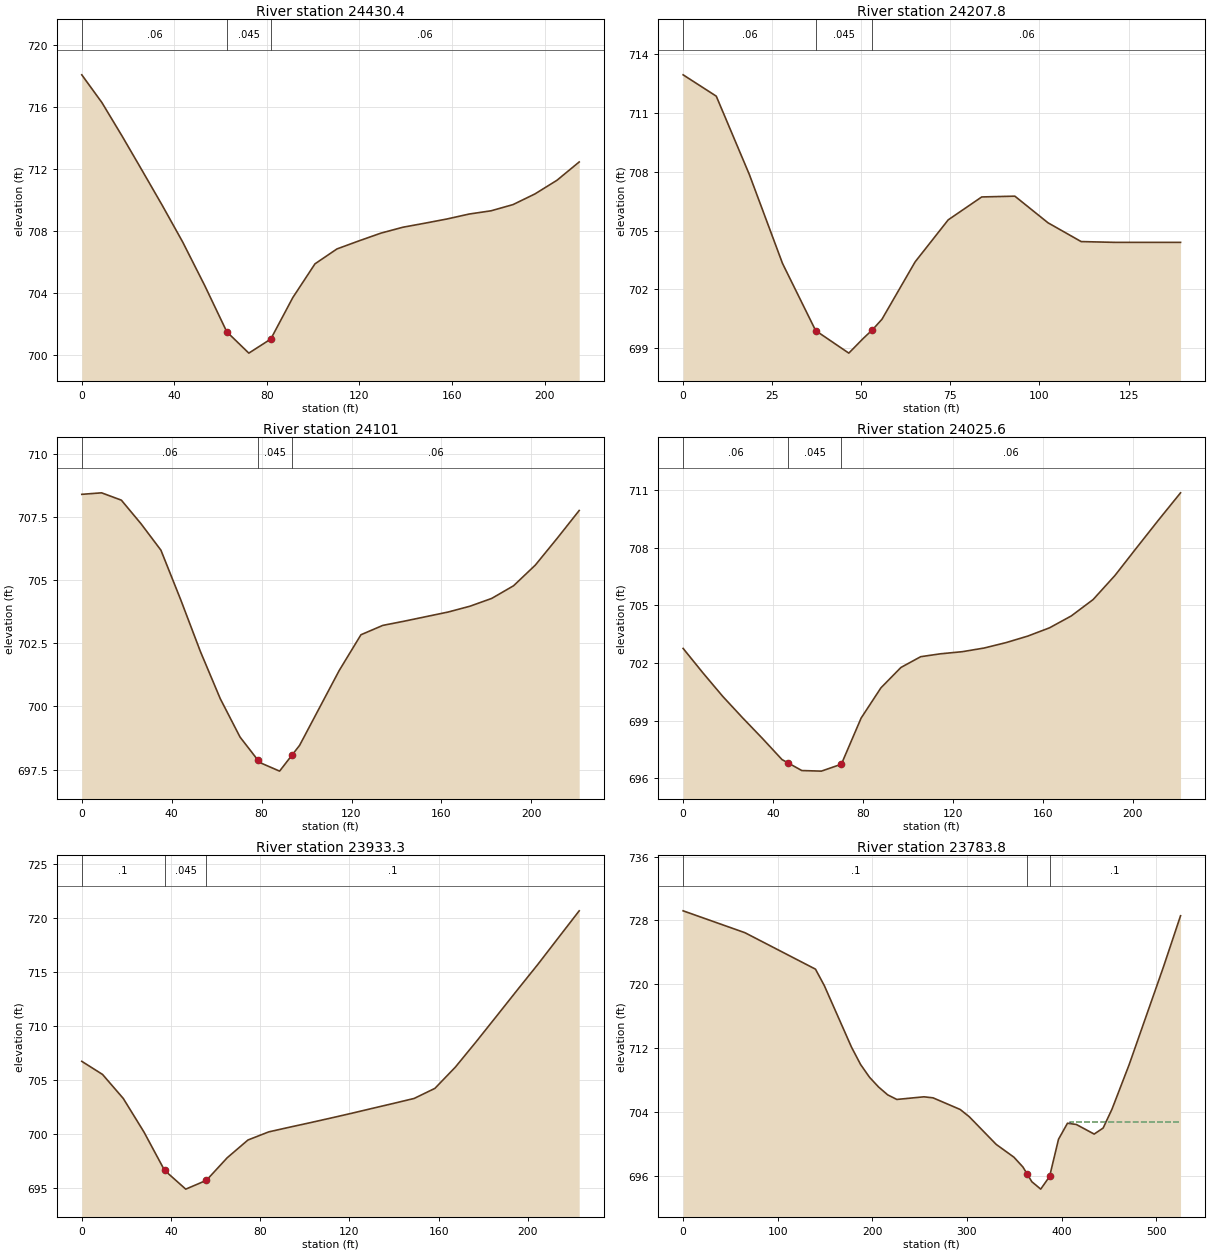
Type RM Length L Ch R = 1 ,24430.4 ,222.8,222.7,222.6
XS GIS Cut Line= 3
     1770110.556      576448.328      1770068.89      576435.307
     1769906.129      576381.921
#Sta/Elev= 26
       0  718.07     8.7  716.28    17.5   714.1    26.2  711.87    34.9  709.62
    43.6  707.29    53.2  704.46    62.7  701.49    64.1  701.29    72.2  700.12
    79.1  700.78    81.7  701.03    91.2   703.7   100.8  705.88   110.3  706.84
   119.8  707.36   129.3  707.86   138.8  708.24   148.3   708.5   157.8  708.77
   167.4  709.09   176.9   709.3   186.4   709.7   195.9  710.39   205.4  711.27
     215  712.45
#Mann= 3 , 0 , 0
       0     .06       0    62.7    .045       0    81.7     .06       0
Bank Sta=62.7,81.7
XS Rating Curve= 0 ,0
Exp/Cntr=0.3,0.1

Type RM Length L Ch R = 1 ,24207.8 ,128.8,106.8,85.3
XS GIS Cut Line= 2
     1770145.712      576226.973       1770012.9      576184.005
#Sta/Elev= 19
       0  712.96     9.3  711.87    18.6  707.86    27.9  703.32    35.6  700.48
    37.2  699.89    46.5  698.74    50.6   699.5   53.07  699.92    55.8  700.47
    65.1   703.4    74.4  705.55    83.8  706.72    93.1  706.76   102.4   705.4
   111.7  704.44     121   704.4   130.3   704.4   139.6   704.4
#Mann= 3 , 0 , 0
       0     .06       0    37.2    .045       0   53.07     .06       0
Bank Sta=37.2,53.07
XS Rating Curve= 0 ,0
Exp/Cntr=0.3,0.1

Type RM Length L Ch R = 1 ,24101   ,83.1,75.4,67.9
XS GIS Cut Line= 4
     1770201.702      576062.911     1770174.358      576085.046
     1770105.348      576124.109     1769998.577      576122.807
#Sta/Elev= 27
       0   708.4     8.8  708.46    17.6  708.17    26.4  707.23    35.2  706.19
      44  704.23    52.8  702.17    61.6  700.31    70.4  698.79    78.4  697.87
    79.2  697.78      88  697.44    93.4  698.06    96.9  698.46   105.7  699.94
   114.5  701.42   124.2  702.84   133.9  703.21   143.6  703.38   153.3  703.56
     163  703.74   172.7  703.97   182.4  704.28   192.1  704.78   201.8   705.6
   211.6  706.67   221.3  707.76
#Mann= 3 , 0 , 0
       0     .06       0    78.4    .045       0    93.4     .06       0
Bank Sta=78.4,93.4
XS Rating Curve= 0 ,0
Exp/Cntr=0.3,0.1

Type RM Length L Ch R = 1 ,24025.6 ,63.1,92.3,120
XS GIS Cut Line= 4
     1770195.192      576006.921     1770167.848      576029.057
     1770098.837      576068.119     1769992.067      576066.817
#Sta/Elev= 26
       0  702.76     8.8  701.49    17.6  700.27    26.4  699.16    35.2  698.09
      44  696.98    46.5  696.82    52.8  696.41    61.5  696.38    70.4  696.74
    79.2  699.14      88  700.71    96.9  701.77   105.7  702.33   114.5  702.48
   124.2  702.59   133.9  702.78   143.6  703.06   153.3   703.4     163  703.83
   172.7  704.45   182.4   705.3   192.1  706.55   201.8     708   211.6  709.45
   221.3  710.85
#Mann= 3 , 0 , 0
       0     .06       0    46.5    .045       0    70.4     .06       0
Bank Sta=46.5,70.4
XS Rating Curve= 0 ,0
Exp/Cntr=0.3,0.1

Type RM Length L Ch R = 1 ,23933.3 ,143.7,149.5,155.7
XS GIS Cut Line= 3
      1770231.65      575966.557     1770079.306      575923.588
     1770020.712      575896.244
#Sta/Elev= 26
       0  706.73     9.3  705.52    18.6   703.3    27.9  700.19    37.1  696.66
    46.6  694.92    52.1   695.4    55.9  695.74    65.2  697.82    74.5  699.46
    83.8  700.21    93.1  700.64   102.4  701.06   111.7  701.49     121  701.93
   130.4  702.39   139.7  702.84     149   703.3   158.3  704.23   167.5   706.2
   176.8  708.54     186  710.92   195.2  713.31   204.5   715.7   213.7  718.16
     223  720.64
#Mann= 3 , 0 , 0
       0      .1       0    37.1    .045       0    55.9      .1       0
Bank Sta=37.1,55.9
XS Rating Curve= 0 ,0
Exp/Cntr=0.3,0.1

Type RM Length L Ch R = 1 ,23783.8 ,94.7,95.7,97
XS GIS Cut Line= 5
     1770382.692      576118.901     1770288.366      576003.235
      1770269.41      575841.557     1770148.317       575768.64
     1770091.025      575724.369
#Sta/Elev= 30
       0   729.2    65.3  726.46   139.9  721.89   149.2  719.84     178  712.11
   187.6  709.94   197.1  708.33   206.7  707.11   216.3  706.13   225.9  705.56
   254.6  705.89   264.2  705.76   292.9   704.3   302.5  703.39   330.9  699.93
   349.7  698.32   359.2  697.09   363.9  696.17   368.6  695.25     378  694.32
   387.4  695.91   396.8  700.57   406.3  702.58   415.7  702.42   434.5  701.22
     444  701.98   453.4  704.36   471.5  709.93   507.7  722.16   525.8  728.58
#Mann= 3 , 0 , 0
       0      .1       0   363.9    .045       0   387.4      .1       0
#XS Ineff= 2 , 0
                          409.21           702.7
Permanent Ineff=
       F       F
Bank Sta=363.9,387.4
XS Rating Curve= 0 ,0
Exp/Cntr=0.3,0.1

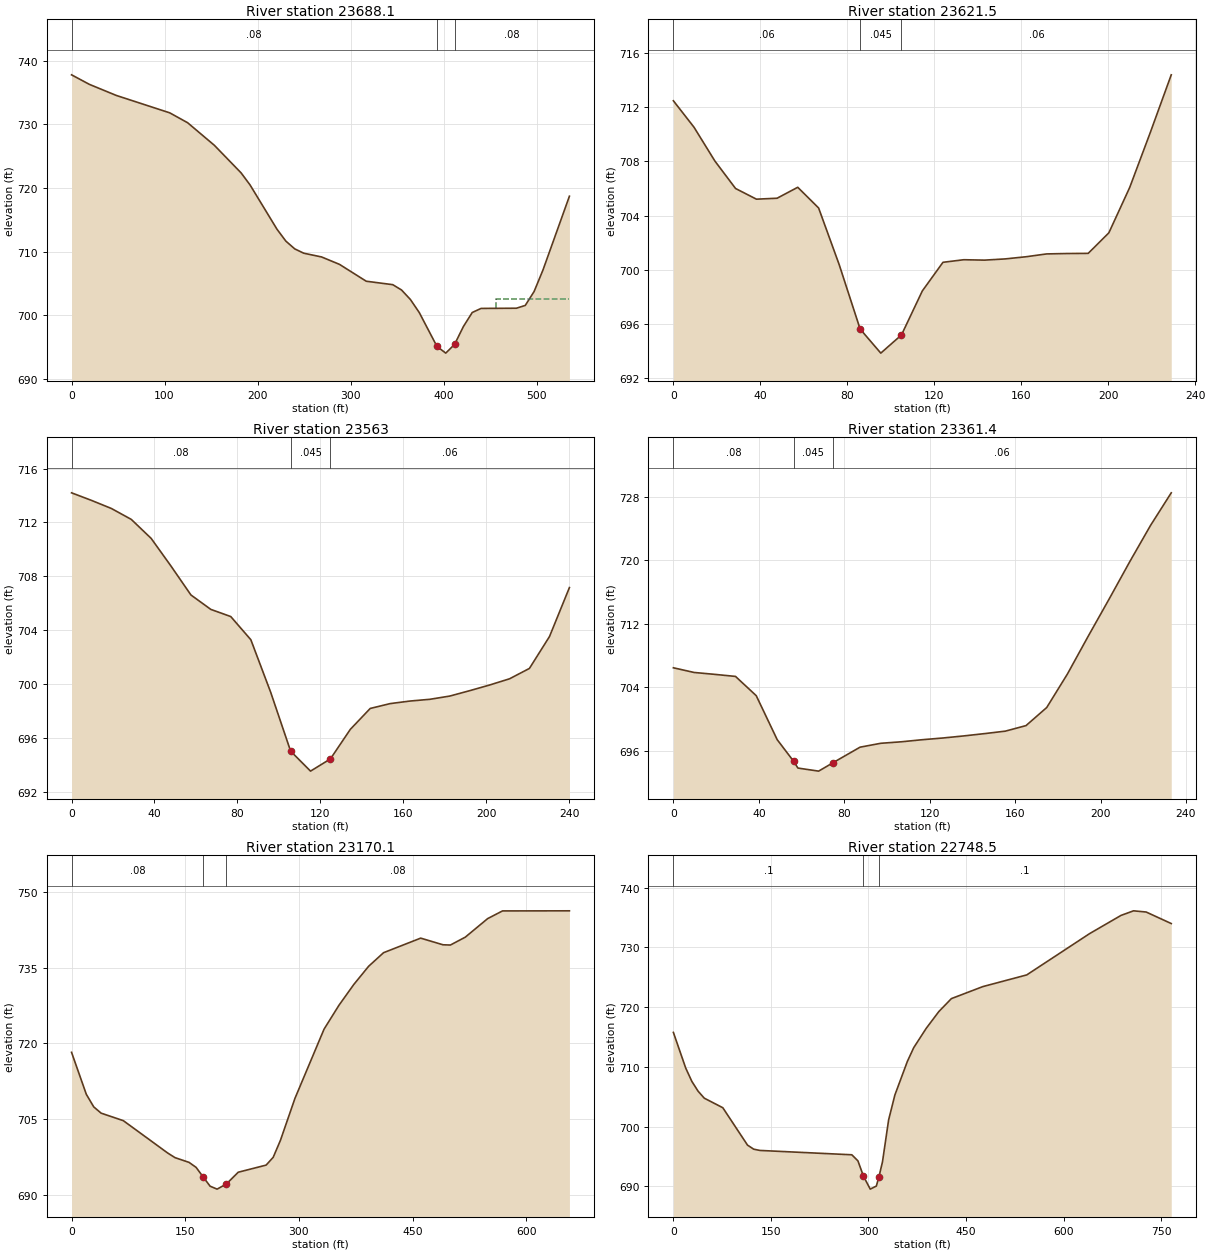
Type RM Length L Ch R = 1 ,23688.1 ,66.4,66.5,66.4
XS GIS Cut Line= 3
     1770584.515      575975.671      1770337.54      575777.128
     1770156.129      575655.359
#Sta/Elev= 30
       0  737.77    19.2  736.27      48  734.54   105.6   731.8   124.8  730.25
   153.6   726.7   182.4  722.36     192  720.47   220.9  713.53   230.5  711.65
   240.1  710.43   249.7  709.76   268.9  709.17   288.1  708.01   316.9  705.36
   345.4  704.82   354.9  703.98   364.4  702.49   373.9  700.45   392.9  695.14
   402.4  694.07   411.9  695.44   421.4  698.25   430.9  700.45   440.4  701.09
   478.4  701.12   487.9  701.56   497.4  703.74   506.9   707.1   535.4  718.71
#Mann= 3 , 0 , 0
       0     .08       0   392.9    .045       0   411.9     .08       0
#XS Ineff= 2 , 0
                          456.51           702.5
Permanent Ineff=
       F       F
Bank Sta=392.9,411.9
XS Rating Curve= 0 ,0
Exp/Cntr=0.3,0.1

Type RM Length L Ch R = 1 ,23621.5 ,58.5,58.6,58.6
XS GIS Cut Line= 2
     1770385.296      575729.578     1770195.192      575601.973
#Sta/Elev= 27
       0  712.49     9.5  710.53    19.1  708.03    28.6     706    38.2  705.21
    47.7  705.28    57.2  706.09    66.8  704.56    76.3  700.35    85.9   695.6
    87.4  695.32    95.4  693.82   102.4  694.81   104.9  695.16   114.5  698.42
     124  700.54   133.6  700.73   143.1   700.7   152.6  700.79   162.2  700.95
   171.7  701.16   181.3  701.19   190.8   701.2   200.3  702.72   209.9  706.08
   219.4  710.16     229  714.41
#Mann= 3 , 0 , 0
       0     .06       0    85.9    .045       0   104.9     .06       0
Bank Sta=85.9,104.9
XS Rating Curve= 0 ,0
Exp/Cntr=0.3,0.1

Type RM Length L Ch R = 1 ,23563   ,215.2,201.6,187.9
XS GIS Cut Line= 2
     1770432.171      575691.817     1770232.952      575557.703
#Sta/Elev= 28
       0   714.2     9.6  713.64    19.2  713.04    28.8  712.23    38.4  710.82
      48  708.76    57.6  706.62    67.2  705.55    76.8  705.02    86.5   703.3
    96.1  699.39   105.7  695.03   109.4  694.46   115.3  693.55   124.4  694.41
   124.9  694.46   134.5  696.65   144.1   698.2   153.7  698.56   163.3  698.75
   172.9  698.88   182.5  699.12   192.1  699.52   201.7  699.94   211.3   700.4
   220.9  701.17   230.6  703.54   240.2  707.17
#Mann= 3 , 0 , 0
       0     .08       0   105.7    .045       0   124.9     .06       0
Bank Sta=105.7,124.9
XS Rating Curve= 0 ,0
Exp/Cntr=0.3,0.1

Type RM Length L Ch R = 1 ,23361.4 ,187.1,191.3,194.7
XS GIS Cut Line= 2
      1770443.89      575430.098     1770210.817      575432.703
#Sta/Elev= 28
       0  706.46     9.7  705.87    19.4  705.63    29.1  705.37    38.8  702.94
    48.6   697.4   56.24  694.69    58.3  693.82    59.7  693.76      68  693.43
    74.7  694.48    77.7  694.95    87.4  696.45    97.1  696.94   106.8  697.13
   116.5  697.39   126.3  697.61     136  697.87   145.7  698.16   155.4  698.47
   165.1  699.17   174.8  701.45   184.5  705.68   194.2  710.43     204  715.12
   213.7  719.85   223.4  724.41   233.1  728.52
#Mann= 3 , 0 , 0
       0     .08       0   56.24    .045       0    74.7     .06       0
Bank Sta=56.24,74.7
XS Rating Curve= 0 ,0
Exp/Cntr=0.3,0.1

Type RM Length L Ch R = 1 ,23170.1 ,402.2,421.6,441.3
XS GIS Cut Line= 5
     1770508.994      575329.838     1770397.015      575251.713
     1770268.108      575239.994     1770204.306      575260.828
     1769898.317      575155.359
#Sta/Elev= 30
       0  718.24    19.5   709.9    29.3  707.41      39  706.17    68.3  704.68
   126.8  698.26   136.5  697.34     155   696.4   164.3  695.41   173.5  693.53
   182.8  691.67     192  691.09   204.3  692.11   219.8  694.44   256.7  695.86
     266   697.4   275.6  700.79   294.7   709.1   333.1  722.84   352.7  727.57
   372.3   731.7   391.9  735.32   411.6  738.02   460.6  740.91     490  739.59
   499.8  739.54   519.4   741.1   548.9  744.78   568.5  746.31   656.8  746.33
#Mann= 3 , 0 , 0
       0     .08       0   173.5    .045       0   204.3     .08       0
Bank Sta=173.5,204.3
XS Rating Curve= 0 ,0
Exp/Cntr=0.3,0.1

Type RM Length L Ch R = 1 ,22748.5 ,219.5,221.5,223.7
XS GIS Cut Line= 4
      1770550.66       575237.39     1770498.577      575125.411
     1770390.504      574948.328     1769963.421      574867.598
#Sta/Elev= 30
       0  715.76      19  709.78    28.5  707.54      38  705.92    47.5  704.75
      76  703.15     114  696.89   123.5  696.21   132.9     696   274.4  695.27
   283.8  694.25   292.3  691.69   302.7  689.52   312.1  690.03  316.03  691.56
   321.5  694.06     331  701.12   340.6  705.28   359.9  710.93   369.6  713.21
   388.9  716.46   408.2  719.25   427.5  721.42   475.8  723.43   543.4  725.39
     640   732.3   688.3  735.35   707.6  736.12     727  735.92   765.6  733.99
#Mann= 3 , 0 , 0
       0      .1       0   292.3    .045       0  316.03      .1       0
Bank Sta=292.3,316.03
XS Rating Curve= 0 ,0
Exp/Cntr=0.3,0.1

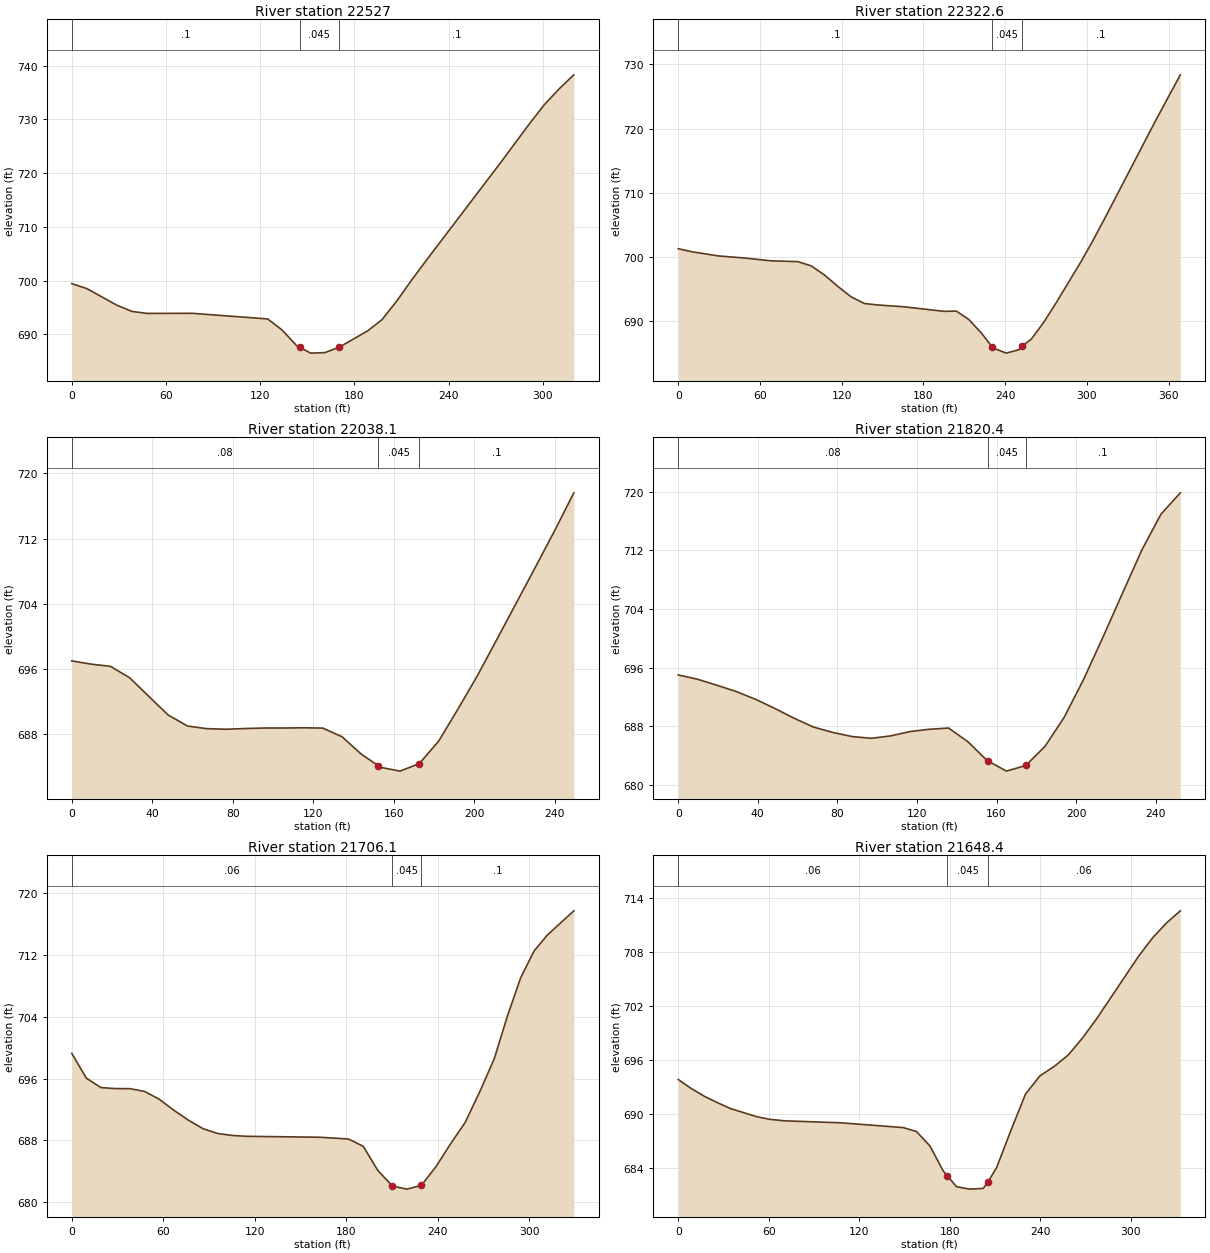
Type RM Length L Ch R = 1 ,22527   ,214,204.3,194.9
XS GIS Cut Line= 4
     1770641.806      574999.109     1770602.744      574880.619
     1770570.192      574815.515      1770475.14      574738.692
#Sta/Elev= 23
       0  699.45     9.6  698.53    28.8  695.43    38.4  694.28      48  693.91
    76.8  693.93   124.8  692.88   133.9  690.84     143  687.99   145.2  687.63
   152.1  686.52   161.2  686.61   170.3  687.61   188.4  690.65   197.6  692.74
     207  696.22   216.4  700.08   225.8  703.78   272.8  721.83   291.6  729.23
     301  732.75   310.4  735.69   319.8  738.31
#Mann= 3 , 0 , 0
       0      .1       0   145.2    .045       0   170.3      .1       0
Bank Sta=145.2,170.3
XS Rating Curve= 0 ,0
Exp/Cntr=0.3,0.1

Type RM Length L Ch R = 1 ,22322.6 ,284.1,284.5,284.8
XS GIS Cut Line= 4
     1770783.733      574920.984     1770745.973      574729.578
     1770682.171      574677.494     1770617.067      574613.692
#Sta/Elev= 30
       0  701.28     9.8  700.82    29.3  700.16    48.8  699.83    68.3  699.39
    87.8  699.27    97.6  698.61   107.3   697.2   117.1  695.42   126.8   693.8
   136.6  692.75   146.3  692.52   165.8  692.23   195.1  691.52   204.2  691.56
   213.4  690.24   222.6  688.13  230.65  685.93   231.7  685.76   240.8  685.01
     250  685.53  252.26  686.06   259.2  687.19   268.3   689.8   277.5  692.87
   295.7  699.26   304.8  702.69   313.9  706.32   350.4  721.22   368.6  728.38
#Mann= 3 , 0 , 0
       0      .1       0  230.65    .045       0  252.26      .1       0
Bank Sta=230.65,252.26
XS Rating Curve= 0 ,0
Exp/Cntr=0.3,0.1

Type RM Length L Ch R = 1 ,22038.1 ,218.7,217.7,216.6
XS GIS Cut Line= 2
     1770980.348      574562.911     1770788.942      574402.755
#Sta/Elev= 29
       0     697     9.6   696.6    19.2  696.33    28.8  694.92    38.4  692.62
      48  690.34    57.6     689    67.2  688.68    76.8  688.61    86.4   688.7
      96  688.76   105.6  688.76   115.2  688.79   124.8  688.75   134.4  687.68
   137.3  687.03     144  685.54   152.3  684.15   153.6  683.93   163.2  683.47
   172.8   684.4   182.4  687.15     192  691.09   201.6  695.16   211.2  699.57
   220.8  704.01   230.4  708.46     240  712.95   249.6  717.62
#Mann= 3 , 0 , 0
       0     .08       0   152.3    .045       0   172.8      .1       0
Bank Sta=152.3,172.8
XS Rating Curve= 0 ,0
Exp/Cntr=0.3,0.1

Type RM Length L Ch R = 1 ,21820.4 ,111.2,114.3,117.3
XS GIS Cut Line= 2
     1771091.025      574372.807     1770891.806      574217.859
#Sta/Elev= 29
       0  695.02     9.7  694.44    19.4  693.62    29.1  692.77    38.8  691.71
    48.5  690.47    58.2  689.13      68  687.92    77.7  687.19    87.4  686.63
    97.1  686.39   106.8  686.72   116.5  687.31   126.2  687.62   135.9  687.79
   145.6  685.93   155.3  683.36   155.8  683.29     165  681.92   170.8  682.38
   174.7  682.69   184.4   685.3   194.1  689.29   203.8  694.42   213.6  700.22
   223.3  706.13     233  712.01   242.7  716.93   252.4  719.83
#Mann= 3 , 0 , 0
       0     .08       0   155.8    .045       0   174.7      .1       0
Bank Sta=155.8,174.7
XS Rating Curve= 0 ,0
Exp/Cntr=0.3,0.1

Type RM Length L Ch R = 1 ,21706.1 ,55,57.7,60.5
XS GIS Cut Line= 3
     1771175.591      574330.619     1770981.146      574133.397
     1770929.063       574135.48
#Sta/Elev= 30
       0  699.25     9.6  696.04    19.1  694.83    28.6   694.7    38.2  694.69
    47.8  694.33    57.3  693.33    66.8  691.92    76.4  690.63      86  689.53
    95.5  688.91     105  688.65   114.6  688.54   162.4  688.42   181.4  688.19
     191  687.26   200.6  684.14   210.2  682.11   219.7  681.72   229.2  682.21
   238.8  684.64   248.3  687.57   257.9  690.34   267.4  694.28     277  698.59
   285.6  704.09   294.3  709.03     303  712.45   311.7  714.52   329.1  717.65
#Mann= 3 , 0 , 0
       0     .06       0   210.2    .045       0   229.2      .1       0
Bank Sta=210.2,229.2
XS Rating Curve= 0 ,0
Exp/Cntr=0.3,0.1

Type RM Length L Ch R = 1 ,21648.4 ,38.5,38.7,46.3
XS GIS Cut Line= 6
     1771161.702      574268.814     1771086.702       574204.23
     1771076.285      574155.619     1771038.091      574107.008
     1771029.758      574069.508     1771026.285      573986.175
#Sta/Elev= 30
       0  693.86     8.6  692.86    17.3     692      26  691.29    34.6  690.64
    51.9  689.74    60.6  689.45    70.3  689.28   107.7  689.06   149.1  688.53
   157.9  688.09   166.8  686.49   175.6  683.72   178.2  683.21   184.4  681.98
   193.2  681.71   202.1  681.79  205.23   682.5   210.9  684.07   220.5  688.23
   230.1  692.24   239.7  694.26   249.3  695.33   258.6   696.6   267.9  698.46
   277.1  700.55   304.9  707.48   314.2  709.53   323.5   711.2   332.7  712.55
#Mann= 3 , 0 , 0
       0     .06       0   178.2    .045       0  205.23     .06       0
Bank Sta=178.2,205.23
XS Rating Curve= 0 ,0
Exp/Cntr=0.3,0.1

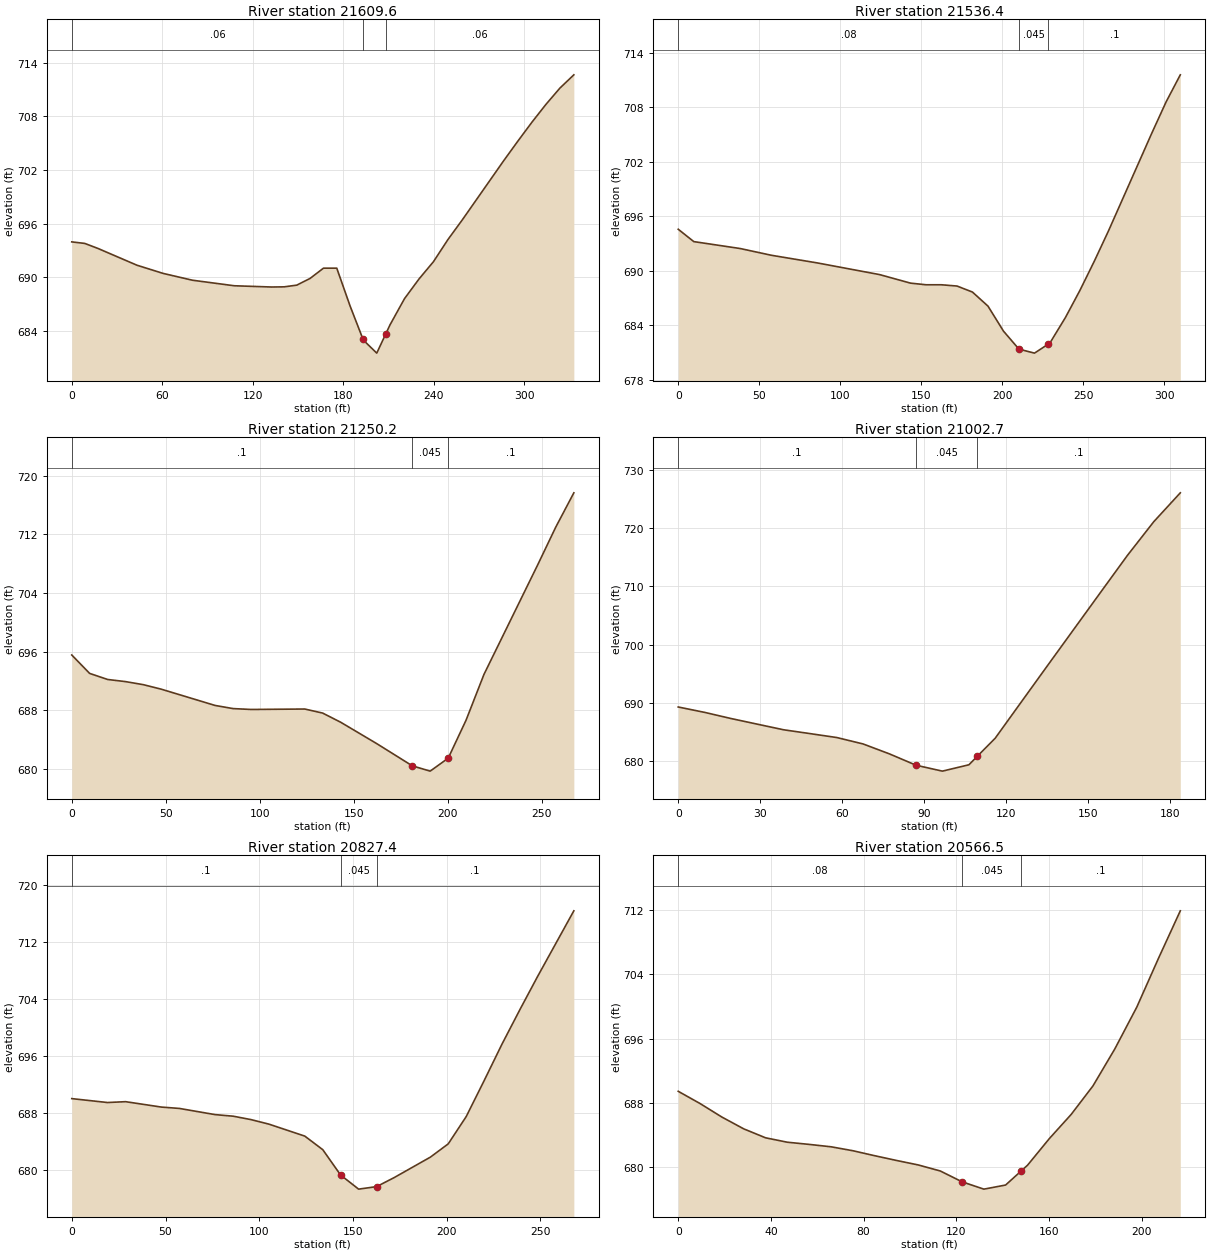
Type RM Length L Ch R = 1 ,21609.6 ,74.2,73.2,67.1
XS GIS Cut Line= 6
     1771190.869      574247.286     1771115.869      574182.703
     1771105.452      574134.092     1771067.258       574085.48
     1771058.924       574047.98     1771055.452      573964.647
#Sta/Elev= 30
       0  693.95     8.6  693.78    17.3  693.22    43.2  691.34    60.6  690.42
      80  689.66   107.7  689.04   132.5   688.9   140.8  688.92   149.1  689.11
   157.9  689.86   166.8  691.01   175.6  691.01   184.4  686.79   192.9  683.09
   193.2  682.96   202.1   681.5   207.9  683.59   210.9  684.67   220.5   687.6
   230.1   689.8   239.7  691.74   249.3  694.22   258.6  696.37   286.4  703.08
   295.7  705.25   304.9  707.34   314.2  709.34   323.5  711.17   332.7  712.65
#Mann= 3 , 0 , 0
       0     .06       0   192.9    .045       0   207.9     .06       0
Bank Sta=192.9,207.9
XS Rating Curve= 0 ,0
Exp/Cntr=0.3,0.1

Type RM Length L Ch R = 1 ,21536.4 ,271,286.2,298.4
XS GIS Cut Line= 3
     1771255.452      574200.758     1771101.285      574018.119
     1771079.063      573950.758
#Sta/Elev= 24
       0  694.59     9.6  693.23    38.2  692.47    57.4  691.73      86  690.88
   124.3   689.6   143.4  688.66     153  688.48   162.5  688.48   172.1  688.34
   181.6  687.68   191.2  686.13   200.8  683.37   210.3   681.4   219.9  680.96
   228.4  681.95   229.4  682.07     239  684.88   247.9  687.85   256.7  691.03
   265.6  694.42   292.2  705.12   301.1  708.59   309.9  711.58
#Mann= 3 , 0 , 0
       0     .08       0   210.3    .045       0   228.4      .1       0
Bank Sta=210.3,228.4
XS Rating Curve= 0 ,0
Exp/Cntr=0.3,0.1

Type RM Length L Ch R = 1 ,21250.2 ,259.3,247.5,236.2
XS GIS Cut Line= 3
     1771363.369      574125.272      1771358.16      573915.637
     1771341.233      573860.949
#Sta/Elev= 21
       0  695.55     9.5  693.04    19.1  692.21    28.6  691.92    38.1   691.5
    47.7  690.88    76.2  688.67    85.8  688.24    95.3  688.12   123.9  688.18
   133.4  687.63     143  686.38     162  683.49   181.1  680.43   190.6  679.71
   200.2  681.48   209.7  686.67   219.2   692.9   247.9  707.91   257.4     713
     267  717.67
#Mann= 3 , 0 , 0
       0      .1       0   181.1    .045       0   200.2      .1       0
Bank Sta=181.1,200.2
XS Rating Curve= 0 ,0
Exp/Cntr=0.3,0.1

Type RM Length L Ch R = 1 ,21002.7 ,174.7,175.3,175.9
XS GIS Cut Line= 2
     1771648.525      573959.908     1771552.171      573803.658
#Sta/Elev= 22
       0  689.28     9.7  688.35    19.3   687.3      29  686.32    38.6  685.36
    48.3   684.7      58  684.03    67.6  682.93    77.3  681.21      87  679.27
    94.3   678.5    96.6  678.26   106.3  679.35   109.3  680.78   115.9  683.91
   125.6  690.24   135.3  696.56   144.9  702.79   154.6  709.08   164.2  715.29
   173.9  721.12   183.6  726.08
#Mann= 3 , 0 , 0
       0      .1       0      87    .045       0   109.3      .1       0
Bank Sta=87,109.3
XS Rating Curve= 0 ,0
Exp/Cntr=0.3,0.1

Type RM Length L Ch R = 1 ,20827.4 ,262,261,259.9
XS GIS Cut Line= 2
     1771832.119      573941.678     1771698.004      573709.908
#Sta/Elev= 23
       0  690.02    19.1  689.47    28.7  689.59    47.8  688.83    57.4  688.64
    76.5  687.77    86.1  687.55    95.6  687.07   105.2  686.43   124.3  684.75
   133.9  682.84   143.4  679.28     153   677.3   162.6  677.65   172.1  678.94
   191.3   681.8   200.8  683.66   210.4   687.5     220  692.57   229.5  697.69
   239.1  702.56   248.6  707.25   267.8  716.41
#Mann= 3 , 0 , 0
       0      .1       0   143.4    .045       0   162.6      .1       0
Bank Sta=143.4,162.6
XS Rating Curve= 0 ,0
Exp/Cntr=0.3,0.1

Type RM Length L Ch R = 1 ,20566.5 ,264.4,266.3,268.7
XS GIS Cut Line= 2
     1772035.244      573764.595     1771918.056      573582.303
#Sta/Elev= 26
       0  689.44     9.4  687.92    18.8  686.24    28.3  684.76    37.7  683.65
    47.1   683.1    56.5  682.83      66  682.53    75.4  682.04    84.8  681.42
    94.2  680.83   103.6  680.27   113.1  679.52   122.5  678.17   131.9  677.26
   132.9  677.31   141.3  677.77   147.9  679.49   150.8  680.25   160.2  683.56
   169.6  686.56     179  690.11   188.4   694.7   197.9  699.91   207.3  706.01
   216.7  711.91
#Mann= 3 , 0 , 0
       0     .08       0   122.5    .045       0   147.9      .1       0
Bank Sta=122.5,147.9
XS Rating Curve= 0 ,0
Exp/Cntr=0.3,0.1

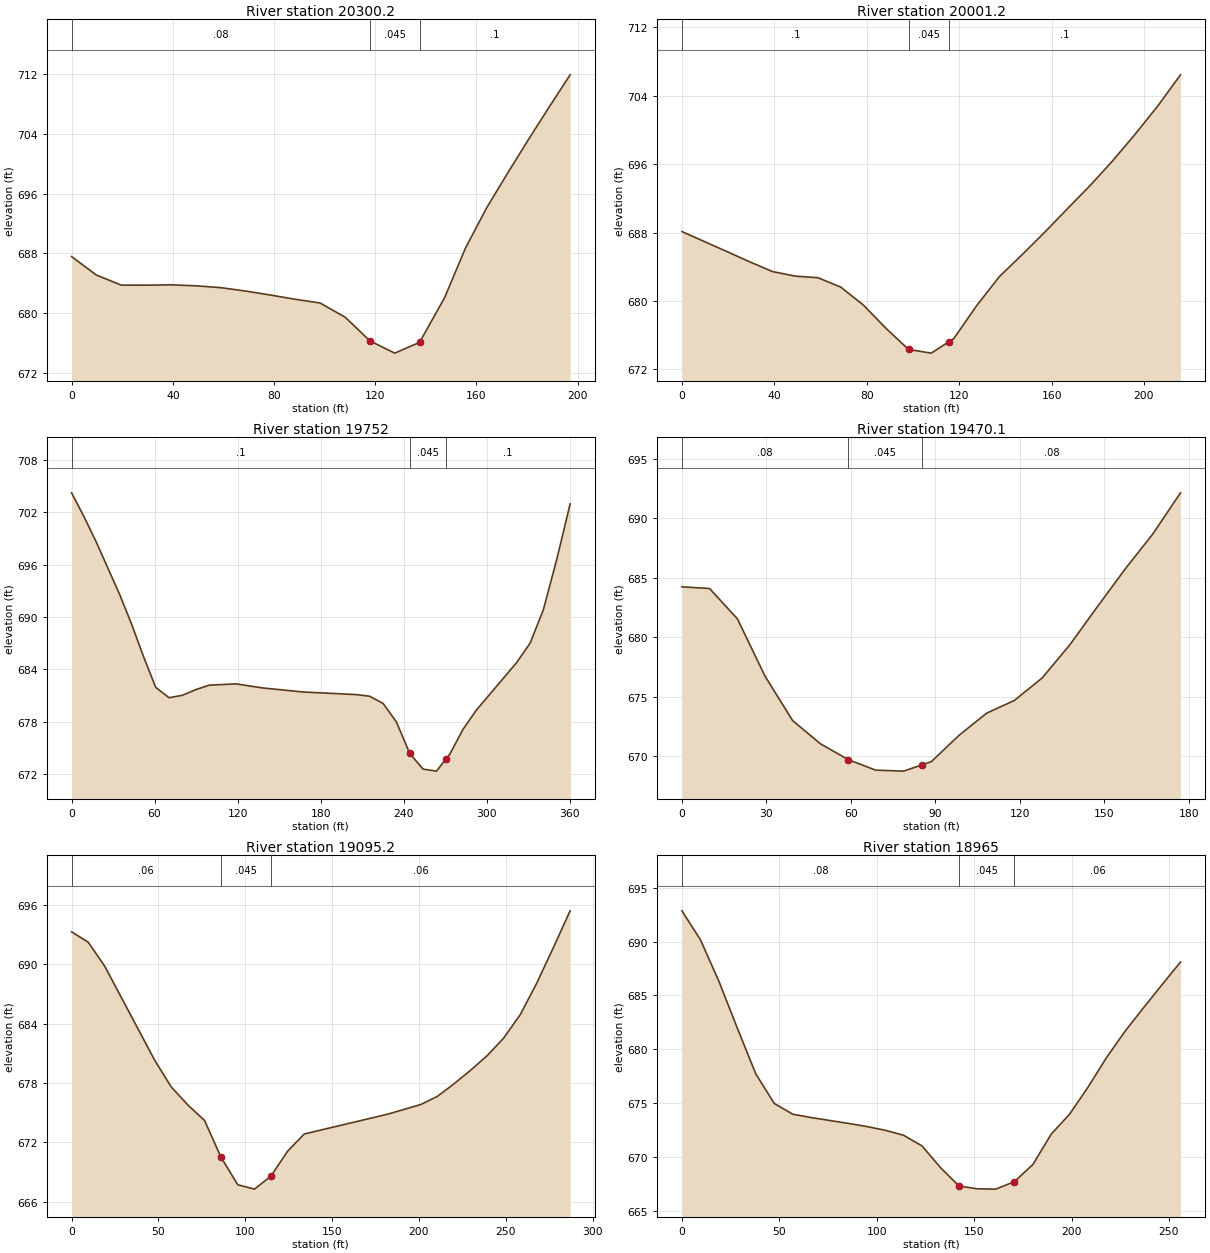
Type RM Length L Ch R = 1 ,20300.2 ,304.7,299,292.8
XS GIS Cut Line= 3
     1772231.858      573600.533     1772162.848      573470.324
     1772143.317      573424.751
#Sta/Elev= 24
       0  687.58     9.8   685.1    19.6  683.75    29.5  683.74    39.3  683.79
    49.1  683.66      59  683.41    68.8  682.95    78.6  682.42    88.4  681.85
    98.2  681.35   108.1  679.45   117.9  676.27   123.8  675.28   127.7  674.63
   137.5  676.07   138.8  676.86   147.4  682.07   155.6  688.68   163.9  694.05
   172.2  698.71   180.4   703.2   188.7  707.62     197  711.95
#Mann= 3 , 0 , 0
       0     .08       0   117.9    .045       0   137.5      .1       0
Bank Sta=117.9,137.5
XS Rating Curve= 0 ,0
Exp/Cntr=0.3,0.1

Type RM Length L Ch R = 1 ,20001.2 ,251.4,249.1,246.9
XS GIS Cut Line= 2
     1772497.483      573410.428     1772354.254       573248.97
#Sta/Elev= 25
       0  688.11     9.8  686.94    19.6  685.76    29.4  684.57    39.2  683.44
      49  682.91    58.9  682.72    68.7  681.63    78.5  679.54    88.3  676.81
    98.1  674.34   100.6  674.23   107.9  673.91   115.6  675.25   117.7  675.62
   127.5  679.43   137.4  682.85   147.2   685.4     157  688.03   166.8  690.77
   176.6  693.47   186.4  696.37   196.2   699.5     206   702.8   215.8  706.43
#Mann= 3 , 0 , 0
       0      .1       0    98.1    .045       0   115.6      .1       0
Bank Sta=98.1,115.6
XS Rating Curve= 0 ,0
Exp/Cntr=0.3,0.1

Type RM Length L Ch R = 1 ,19752   ,287.8,281.9,275.3
XS GIS Cut Line= 3
     1772748.785      573345.324     1772738.369      573285.428
     1772517.015      573083.605
#Sta/Elev= 30
       0  704.22     8.7  701.57    17.4  698.73    34.7  692.59    43.4  689.16
    52.1  685.41    60.8  681.93    70.5  680.74    80.1  681.02    89.8  681.67
    99.4  682.18   118.8  682.33   138.1  681.86   167.1   681.4   205.7   681.1
   215.4  680.91   225.1  680.09   234.7  677.98   244.4  674.36     254  672.56
   263.7  672.33   270.7  673.74   273.4  674.29     283  677.15   292.7  679.35
   321.7  684.78   331.4     687     341  690.85   350.7  696.63   360.3  702.95
#Mann= 3 , 0 , 0
       0      .1       0   244.4    .045       0   270.7      .1       0
Bank Sta=244.4,270.7
XS Rating Curve= 0 ,0
Exp/Cntr=0.3,0.1

Type RM Length L Ch R = 1 ,19470.1 ,375.3,374.9,374.8
XS GIS Cut Line= 2
     1772833.421      572965.116     1772675.869      572884.387
#Sta/Elev= 21
       0  684.23     9.8  684.09    19.7  681.54    29.5  676.73    39.3     673
    49.2  671.05      59  669.73    68.8  668.84    70.4  668.83    78.7  668.76
    85.4   669.3    88.5  669.55    98.4  671.77   108.2  673.63     118  674.69
   127.9  676.58   137.7  679.36   147.5  682.56   157.4  685.74   167.2  688.67
     177  692.12
#Mann= 3 , 0 , 0
       0     .08       0      59    .045       0    85.4     .08       0
Bank Sta=59,85.4
XS Rating Curve= 0 ,0
Exp/Cntr=0.3,0.1

Type RM Length L Ch R = 1 ,19095.2 ,126.3,130.2,143.8
XS GIS Cut Line= 2
     1773049.567       572661.73     1772791.754      572535.428
#Sta/Elev= 24
       0  693.28     9.6  692.23    19.1   689.8    47.8  680.33    57.4  677.61
      67  675.78    76.6  674.22      86  670.53    95.7  667.73   105.3  667.29
   114.8   668.6   124.4  671.12     134  672.86   181.8  674.85     201  675.83
   210.5  676.64   220.1  677.91   229.7  679.28   239.2  680.75   248.8  682.54
   258.4  684.92     268  688.14   277.5   691.7   287.1   695.4
#Mann= 3 , 0 , 0
       0     .06       0      86    .045       0   114.8     .06       0
Bank Sta=86,114.8
XS Rating Curve= 0 ,0
Exp/Cntr=0.3,0.1

Type RM Length L Ch R = 1 ,18965   ,323.6,320.8,307.8
XS GIS Cut Line= 2
     1773084.723      572575.793     1772865.973       572442.98
#Sta/Elev= 30
       0  692.86     9.5  690.17      19   686.3    28.4  681.97    37.9  677.71
    47.4  674.96    56.9  673.96    66.4  673.65    75.8  673.38    85.3  673.11
    94.8  672.82   104.3  672.47   113.7  672.01   123.2  671.02   132.7     669
   142.2  667.29   146.9  667.16   151.6  667.03   161.1     667   161.9  667.06
   170.6  667.69   180.1  669.28   189.6  672.12     199  673.97   208.5  676.49
     218  679.24   227.5  681.68     237  683.87   246.4  685.99   255.9   688.1
#Mann= 3 , 0 , 0
       0     .08       0   142.2    .045       0   170.6     .06       0
Bank Sta=142.2,170.6
XS Rating Curve= 0 ,0
Exp/Cntr=0.3,0.1