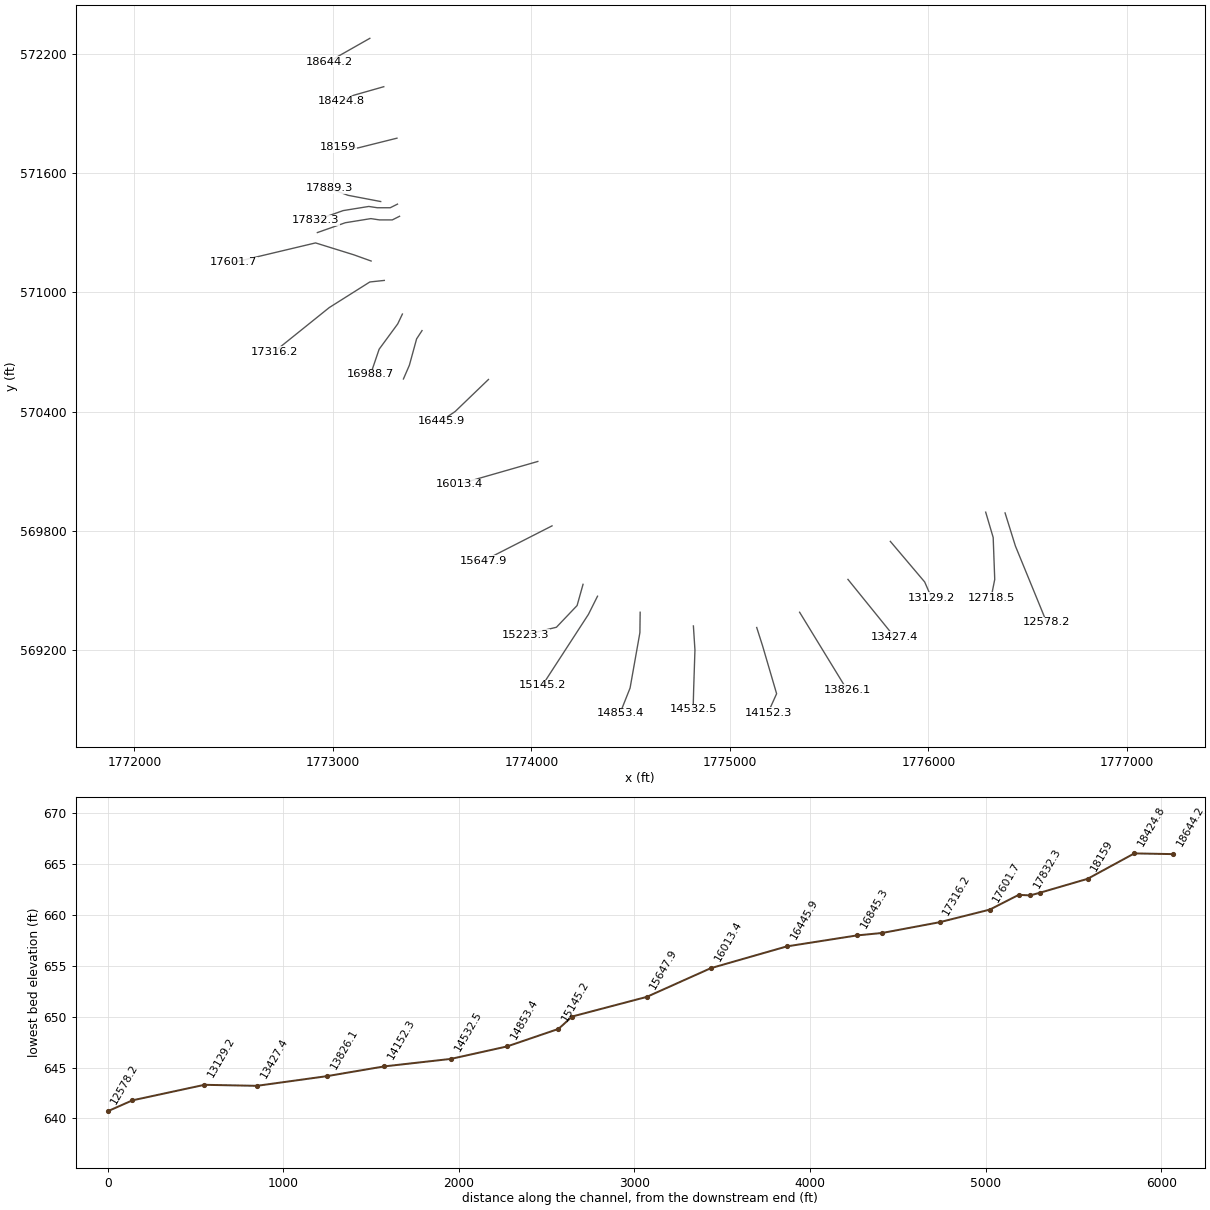
HEC-RAS study ALLENFK.prj: ALLENFK

--- ALLENFK.g01 (geometry) --- (continued)

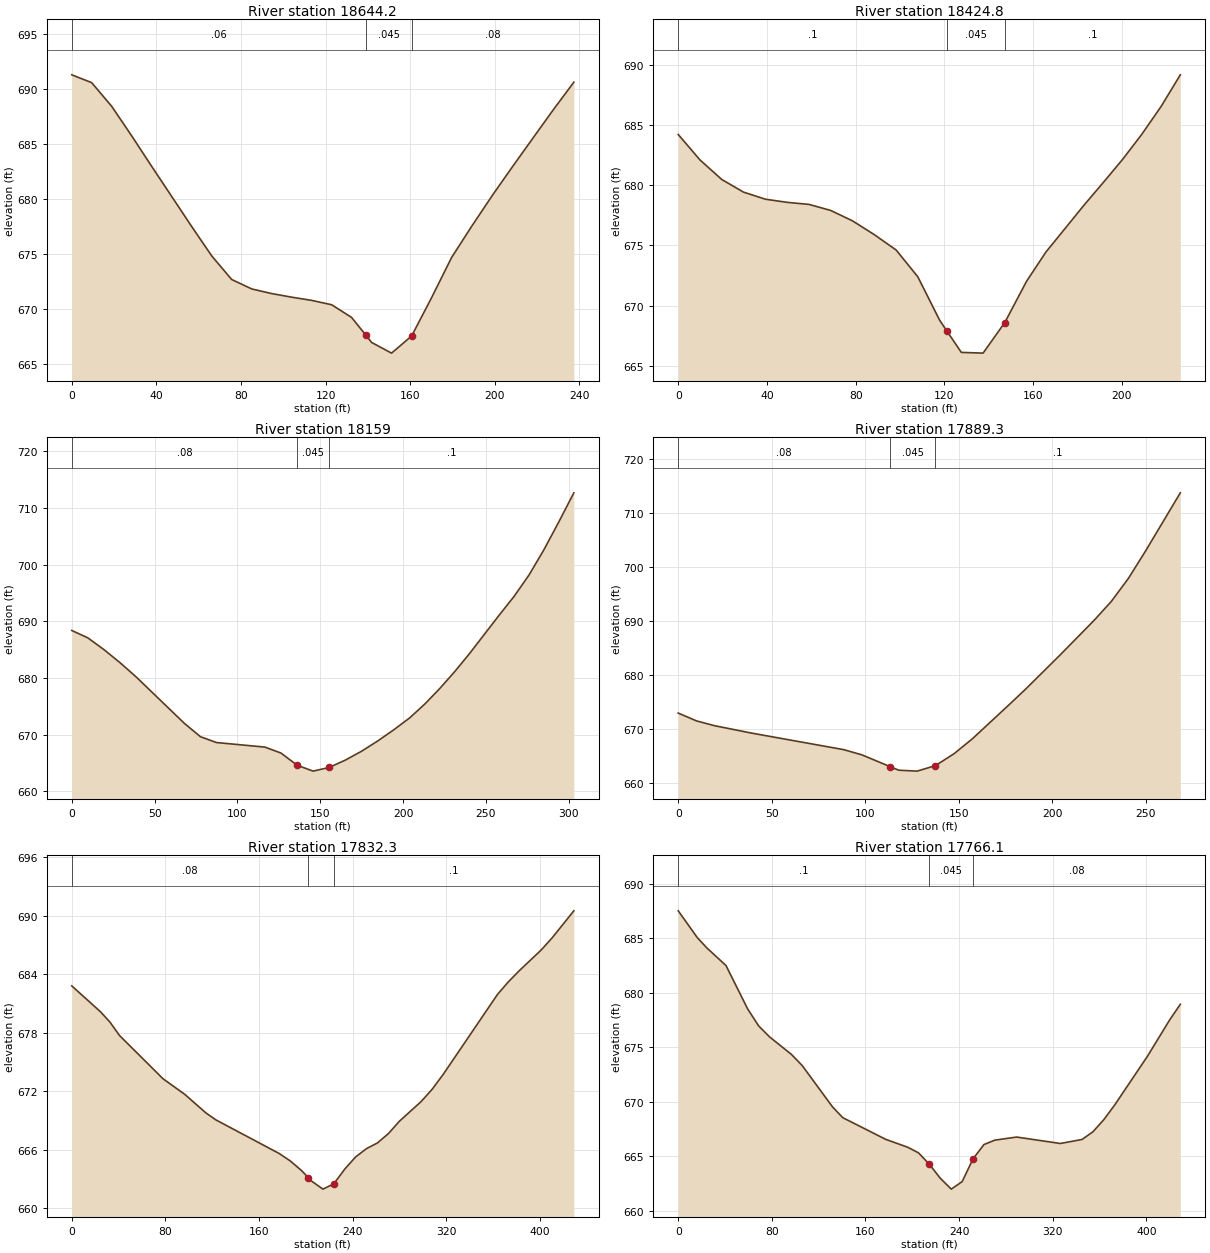
Type RM Length L Ch R = 1 ,18644.2 ,224.8,219.4,214
XS GIS Cut Line= 3
     1773186.285      572278.918     1773030.035      572190.376
     1772980.556      572160.428
#Sta/Elev= 28
       0  691.32     9.4  690.61    18.9  688.45    28.4  685.75    37.8  682.99
    47.3  680.24    56.7  677.52    66.2  674.84    75.6   672.7    85.1  671.84
    94.5  671.42     104  671.09   113.4   670.8   122.9   670.4   132.3  669.25
   138.9  667.67   141.8  666.97   151.2     666   153.9  666.44   160.7  667.56
   170.1  671.03   179.6   674.7   189.2  677.57   198.9  680.36   208.5  682.99
   218.2   685.6   227.8  688.17   237.4  690.65
#Mann= 3 , 0 , 0
       0     .06       0   138.9    .045       0   160.7     .08       0
Bank Sta=138.9,160.7
XS Rating Curve= 0 ,0
Exp/Cntr=0.3,0.1

Type RM Length L Ch R = 1 ,18424.8 ,265.1,265.8,266.5
XS GIS Cut Line= 3
     1773256.598      572035.428     1773105.556       571992.46
     1773043.056      571962.512
#Sta/Elev= 27
       0  684.21     9.8   682.1    19.6  680.48    29.4  679.43    39.3  678.84
    49.1  678.58    58.9  678.41    68.7  677.91    78.5  677.05    88.3  675.91
    98.2  674.63     108   672.4   117.8  668.81     121  667.93   127.6  666.13
     136  666.08   137.4  666.07   147.2  668.61     157  672.03   165.7  674.45
   174.4  676.42     183  678.37   191.7  680.25   200.4  682.17     209  684.24
   217.7  686.55   226.3  689.16
#Mann= 3 , 0 , 0
       0      .1       0     121    .045       0   147.2      .1       0
Bank Sta=121,147.2
XS Rating Curve= 0 ,0
Exp/Cntr=0.3,0.1

Type RM Length L Ch R = 1 ,18159   ,281.3,269.7,258.3
XS GIS Cut Line= 3
     1773323.004      571776.314     1773125.087      571726.835
     1773026.129      571732.043
#Sta/Elev= 28
       0  688.38     9.7  687.08    19.4  685.01    29.1  682.71    38.9  680.18
      68  671.99    77.7  669.64    87.4  668.61   116.6  667.81   126.3  666.76
     136  664.62   145.7  663.57   155.4  664.22   165.2  665.52   174.9  667.07
   184.6  668.87   194.3  670.84     204  672.96     213  675.37     222  678.09
     231  681.06     240  684.26   258.1  691.11   267.1  694.42   276.1  698.19
   285.1  702.65   294.1  707.57   303.1  712.66
#Mann= 3 , 0 , 0
       0     .08       0     136    .045       0   155.4      .1       0
Bank Sta=136,155.4
XS Rating Curve= 0 ,0
Exp/Cntr=0.3,0.1

Type RM Length L Ch R = 1 ,17889.3 ,48.9,57,64.7
XS GIS Cut Line= 3
     1773240.973      571457.303      1773076.91      571488.553
     1772981.858       571523.71
#Sta/Elev= 20
       0  672.95     9.8   671.5    19.6   670.6    39.3  669.24    88.4  666.19
    98.2  665.22   113.3  663.04   117.9  662.38   127.7  662.21   137.5  663.23
   147.4  665.42   157.2  668.18   176.2  674.28   185.4  677.28   203.9  683.62
   222.3   690.1   231.5   693.6   240.7  697.89   249.9  702.98   268.4   713.7
#Mann= 3 , 0 , 0
       0     .08       0   113.3    .045       0   137.5      .1       0
Bank Sta=113.3,137.5
XS Rating Curve= 0 ,0
Exp/Cntr=0.3,0.1

Type RM Length L Ch R = 1 ,17832.3 ,65.7,66.2,66.7
XS GIS Cut Line= 6
     1773325.608      571444.283      1773289.15      571426.053
     1773224.046      571426.053     1773181.077      571432.564
     1773052.171       571411.73     1772911.546      571362.251
#Sta/Elev= 30
       0  682.79    24.5  680.14    32.6  679.08    40.8   677.7      78  673.26
    96.6  671.66   114.6  669.76   123.2  669.04   177.3  665.59   186.6  664.84
     196  663.88   202.1  663.13   205.3  662.73   214.6  661.94   223.9  662.48
   233.3     664   242.6  665.25   251.9   666.1   261.2  666.68   270.6  667.64
   279.9   668.9   298.5  670.92   307.9  672.18   317.2  673.68   363.8  681.92
   373.1  683.21   382.4  684.35     401  686.46   410.4  687.71     429  690.49
#Mann= 3 , 0 , 0
       0     .08       0   202.1    .045       0   223.9      .1       0
Bank Sta=202.1,223.9
XS Rating Curve= 0 ,0
Exp/Cntr=0.3,0.1

Type RM Length L Ch R = 1 ,17766.1 ,175.3,164.4,153.6
XS GIS Cut Line= 6
     1773336.025      571383.085     1773299.567      571364.855
     1773234.462      571364.855     1773191.494      571371.366
     1773062.587      571350.533     1772921.962      571301.053
#Sta/Elev= 30
       0  687.54    16.3  685.08    24.5  684.13    40.8  682.52    59.4  678.52
    68.7  676.98      78  675.97    96.6  674.37   105.9  673.34   131.9  669.53
   140.6  668.55   177.3  666.56     196  665.84   205.3  665.32   214.6  664.27
   223.9  662.99   233.3  661.99   242.6  662.68   251.9  664.77   261.2  666.08
   270.6  666.49   289.2  666.77   326.5  666.18   345.1  666.55   354.4  667.26
   363.8  668.39   373.1  669.74     401   674.2   419.7  677.49     429  678.96
#Mann= 3 , 0 , 0
       0      .1       0   214.6    .045       0   251.9     .08       0
Bank Sta=214.6,251.9
XS Rating Curve= 0 ,0
Exp/Cntr=0.3,0.1

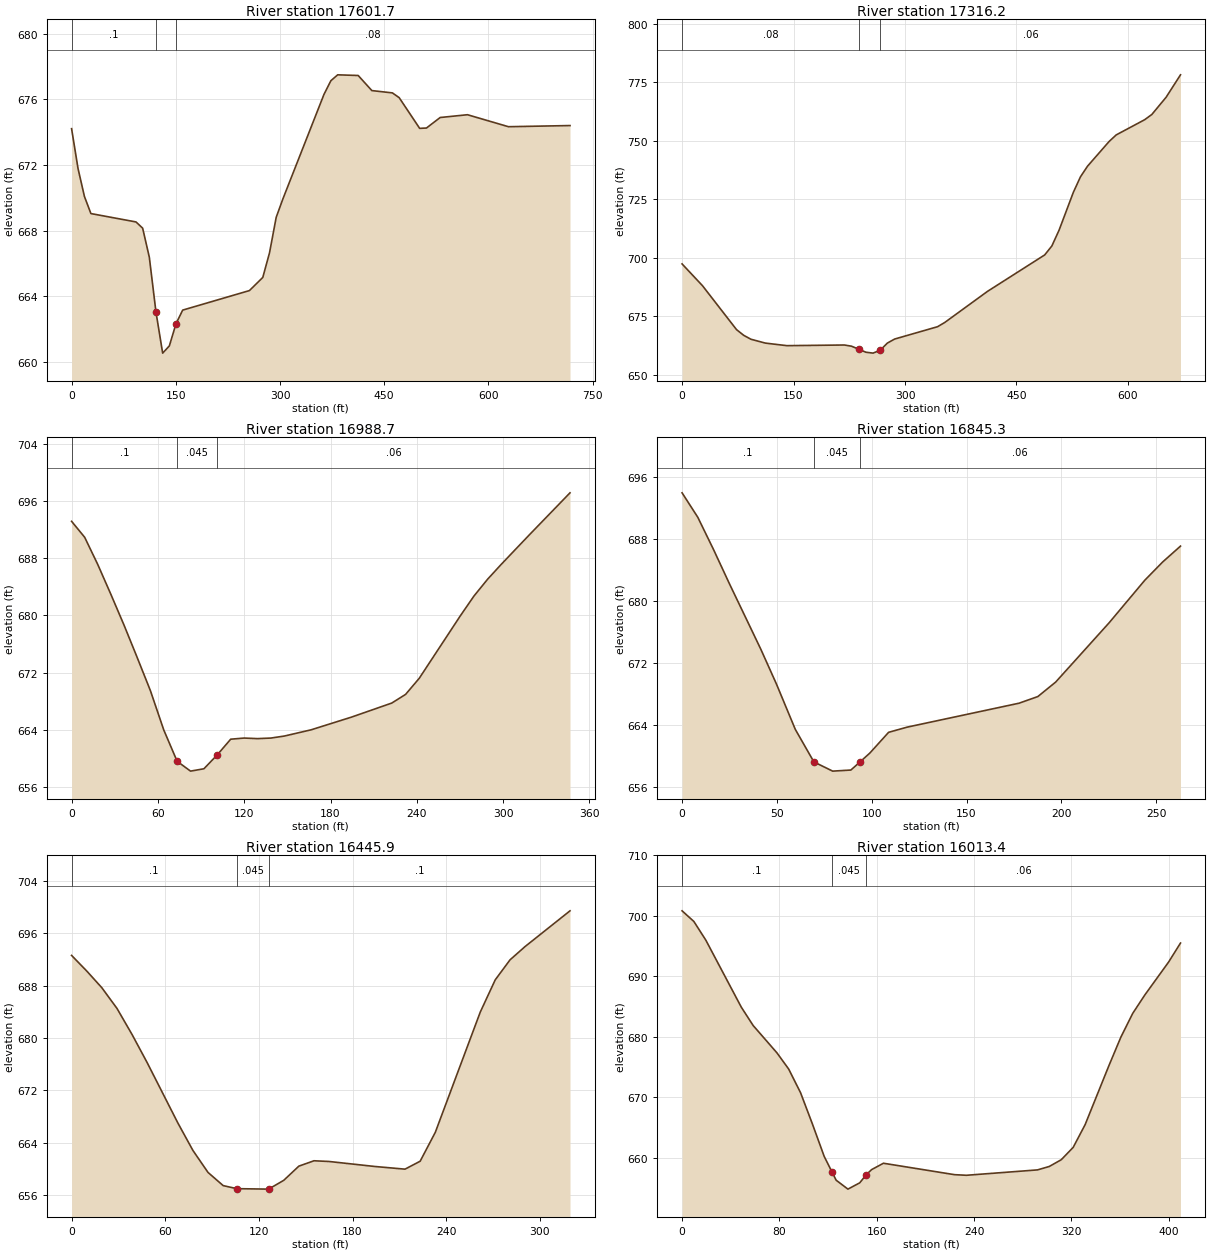
Type RM Length L Ch R = 1 ,17601.7 ,266,285.5,304.9
XS GIS Cut Line= 4
     1773192.796      571157.824     1773105.556      571189.074
     1772912.848       571248.97      1772501.39      571151.314
#Sta/Elev= 30
       0  674.21     9.3  671.78    18.5  670.08    27.8  669.04    92.7  668.53
   102.3  668.15   111.9  666.38   121.5  663.03   131.1  660.54   140.7  660.98
   150.3  662.33   159.9  663.16     256  664.35   275.2  665.15   284.9  666.65
   294.5  668.81   304.3  669.95   363.3   676.3   373.2  677.13     383  677.49
   412.5  677.45   432.2  676.53   461.7  676.39   471.5   676.1     501  674.23
   510.8  674.25   530.5  674.89   569.8  675.06   628.8  674.33   717.4   674.4
#Mann= 3 , 0 , 0
       0      .1       0   121.5    .045       0   150.3     .08       0
Bank Sta=121.5,150.3
XS Rating Curve= 0 ,0
Exp/Cntr=0.3,0.1

Type RM Length L Ch R = 1 ,17316.2 ,318.8,327.6,335.7
XS GIS Cut Line= 4
     1773259.202      571060.168     1773186.285      571052.355
     1772981.858      570923.449     1772704.515      570700.793
#Sta/Elev= 30
       0  697.42    27.5   688.1    73.3  669.34      83   666.9    92.7  665.23
     112  663.59     141  662.49   218.3  662.77     228  662.26   237.7  660.98
   247.3  659.69     257   659.3   266.6  660.54   276.3   663.6     286  665.31
   343.8  670.59   353.5   672.4   411.1  685.71     488  701.27   497.6  705.09
   507.3  711.83   526.5  727.99   536.1  734.64   545.7  739.22   574.6  749.72
   584.2  752.54   622.6  759.06   632.2   761.3   651.4  768.66   670.7  778.22
#Mann= 3 , 0 , 0
       0     .08       0   237.7    .045       0   266.6     .06       0
Bank Sta=237.7,266.6
XS Rating Curve= 0 ,0
Exp/Cntr=0.3,0.1

Type RM Length L Ch R = 1 ,16988.7 ,133.8,143.4,152.5
XS GIS Cut Line= 4
     1773350.348      570890.897      1773326.91      570841.418
      1773233.16      570713.814     1773190.192      570587.512
#Sta/Elev= 28
       0  693.14     9.1  690.91    18.2  687.11    27.4   682.9    36.5  678.62
    45.6  674.12    54.8  669.48    64.1  663.98    73.4  659.61    82.7  658.24
      92  658.57   101.3  660.52   110.6   662.7     120  662.86   129.3  662.78
   138.6  662.86   147.9  663.14   166.5  664.01   194.5  665.78   222.6  667.75
   232.2  668.96   241.7  671.21   270.3  679.95   279.8  682.72   289.3  685.07
   298.8  687.15   317.9  691.18   346.5  697.12
#Mann= 3 , 0 , 0
       0      .1       0    73.4    .045       0   101.3     .06       0
Bank Sta=73.4,101.3
XS Rating Curve= 0 ,0
Exp/Cntr=0.3,0.1

Type RM Length L Ch R = 1 ,16845.3 ,414,399.4,382.7
XS GIS Cut Line= 4
     1773449.306      570807.564     1773421.962      570765.897
     1773385.504      570633.085     1773355.556      570564.074
#Sta/Elev= 21
       0  693.93     8.3  690.77    16.6   686.6    24.9  682.23    41.5  673.75
    49.8  669.22    59.7  663.39    69.5  659.19    79.4     658      89  658.14
    93.8  659.18      99  660.33   108.9  663.01   118.7  663.68   177.7  666.77
   187.6  667.63     197   669.5   225.2  677.16     244  682.65   253.4     685
   262.8  687.05
#Mann= 3 , 0 , 0
       0      .1       0    69.5    .045       0    93.8     .06       0
Bank Sta=69.5,93.8
XS Rating Curve= 0 ,0
Exp/Cntr=0.3,0.1

Type RM Length L Ch R = 1 ,16445.9 ,443.4,432.6,421.4
XS GIS Cut Line= 3
     1773783.942       570561.47     1773615.973      570400.012
     1773544.358      570351.835
#Sta/Elev= 25
       0  692.61     9.7  690.23    19.4  687.67    29.1  684.51    38.8  680.51
    48.5   676.2      68  667.06    77.7  662.84    87.4  659.47    97.1  657.46
   105.8  656.99   126.2  656.92   135.9  658.26   145.6  660.43   155.3  661.25
     165  661.14   194.2  660.38   213.6  659.97   223.3  661.18     233  665.59
   261.8  683.95   271.4  688.88   280.9  691.94   290.5  693.96   319.3  699.42
#Mann= 3 , 0 , 0
       0      .1       0   105.8    .045       0   126.2      .1       0
Bank Sta=105.8,126.2
XS Rating Curve= 0 ,0
Exp/Cntr=0.3,0.1

Type RM Length L Ch R = 1 ,16013.4 ,361.4,365.4,369.2
XS GIS Cut Line= 3
      1774032.64       570148.71      1773733.16      570062.772
      1773639.41      570034.126
#Sta/Elev= 30
       0   700.8     9.7  699.04    19.5  695.96    48.7  684.86    58.4  681.84
    77.9  677.33    87.6  674.64    97.4  670.71   107.1  665.56   116.8  660.19
  123.12  657.65   126.6  656.26   136.3  654.78     146  655.82  151.46  657.19
   155.8  658.01   165.5  659.06   223.9  657.17   233.7  657.07   292.1  657.96
   301.8  658.53   311.6  659.64   321.4  661.68   331.2  665.43   350.8  675.21
   360.6  679.91   370.4  683.86   380.2  686.86   399.8  692.32   409.6  695.47
#Mann= 3 , 0 , 0
       0      .1       0  123.12    .045       0  151.46     .06       0
Bank Sta=123.12,151.46
XS Rating Curve= 0 ,0
Exp/Cntr=0.3,0.1

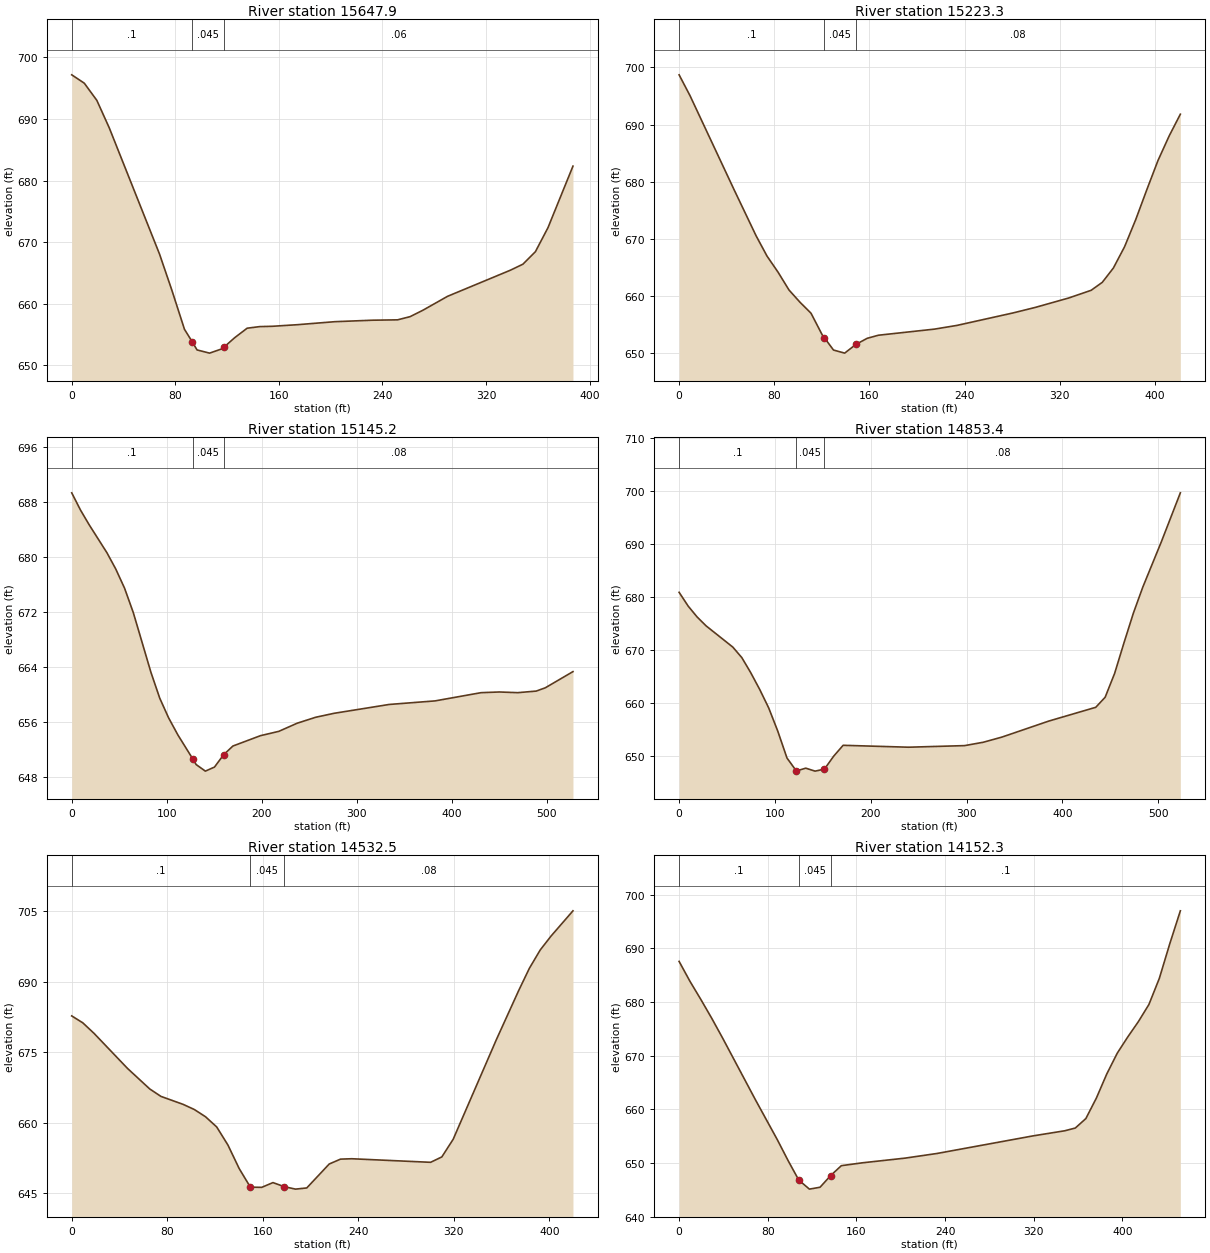
Type RM Length L Ch R = 1 ,15647.9 ,415.3,424.6,432.2
XS GIS Cut Line= 2
     1774104.254      569824.491     1773759.202       569648.71
#Sta/Elev= 28
       0  697.18     9.7  695.82    19.4  693.03      29  688.56    67.8  668.06
    77.4  662.15    87.1  655.82   93.18  653.76    96.8  652.47   106.5  651.95
   116.2  652.66   117.5   652.9   125.9  654.46   135.5     656   145.2  656.26
   154.9  656.31   174.3  656.57   203.3  657.06   232.4   657.3   251.7  657.36
   261.4  657.88   271.1   658.9   290.4  661.19   338.8  665.42   348.5   666.4
   358.2  668.44   367.9  672.34   387.2  682.34
#Mann= 3 , 0 , 0
       0      .1       0   93.18    .045       0   117.5     .06       0
Bank Sta=93.18,117.5
XS Rating Curve= 0 ,0
Exp/Cntr=0.3,0.1

Type RM Length L Ch R = 1 ,15223.3 ,75.7,78.2,82.4
XS GIS Cut Line= 4
     1774260.504       569530.22     1774230.556      569423.449
      1774126.39      569314.074     1773971.442      569276.314
#Sta/Elev= 30
       0  698.71     9.2  695.05    46.2  678.62    64.7  670.56    73.9     667
    83.2  664.18    92.4  661.06   101.6  658.93   110.9     657   120.3  653.22
   122.2  652.69   129.8  650.56   139.2  650.02   148.6  651.54   158.1  652.61
   167.5  653.15   214.7  654.22   233.6  654.87   280.7  657.05   299.5  658.02
   327.6  659.67   346.4  661.01   355.8  662.41   365.1  664.91   374.5  668.63
   383.9  673.39   393.3  678.66   402.6  683.72     412  688.02   421.4  691.82
#Mann= 3 , 0 , 0
       0      .1       0   122.2    .045       0   148.6     .08       0
Bank Sta=122.2,148.6
XS Rating Curve= 0 ,0
Exp/Cntr=0.3,0.1

Type RM Length L Ch R = 1 ,15145.2 ,282.2,291.8,301.2
XS GIS Cut Line= 3
     1774333.421      569470.324     1774287.848      569379.178
     1774056.077      569022.408
#Sta/Elev= 30
       0  689.38     9.3  686.85    18.5  684.69    37.1  680.63    46.3  678.28
    55.6  675.47    64.8  671.91    83.4  663.18    92.6  659.44   101.9  656.58
   111.6   654.1   127.2  650.62   130.9  649.76   140.6   648.8   150.2  649.39
   159.9   651.2   169.6  652.46   198.6  653.97   217.9   654.6   237.3  655.79
   256.6  656.65     276  657.23     334  658.52   382.3  659.04   430.7  660.24
     450  660.34   469.3  660.24   488.7  660.47   498.3  660.95   527.4  663.31
#Mann= 3 , 0 , 0
       0      .1       0   127.2    .045       0   159.9     .08       0
Bank Sta=127.2,159.9
XS Rating Curve= 0 ,0
Exp/Cntr=0.3,0.1

Type RM Length L Ch R = 1 ,14853.4 ,314,320.9,325.7
XS GIS Cut Line= 4
     1774548.265      569389.595     1774546.962       569286.73
     1774497.483      569008.085     1774446.702       568880.48
#Sta/Elev= 30
       0  680.87     9.4  678.28    18.7  676.23    28.1  674.54    56.1  670.51
    65.5  668.52    74.8  665.67    84.2  662.49    93.5  659.03   102.9  654.68
   112.6  649.56   122.4  647.11   132.2  647.64   141.9  647.08   151.7  647.46
   161.4  649.92   171.2  651.96   239.5   651.6     298   651.9   317.6  652.54
   337.1  653.52   385.9  656.54   434.9  659.14   444.7  661.04   454.6  665.55
   464.4  671.35   474.2  676.95     484  681.85   503.6  690.53   523.2  699.67
#Mann= 3 , 0 , 0
       0      .1       0   122.4    .045       0   151.7     .08       0
Bank Sta=122.4,151.7
XS Rating Curve= 0 ,0
Exp/Cntr=0.3,0.1

Type RM Length L Ch R = 1 ,14532.5 ,376.9,380.2,385.4
XS GIS Cut Line= 4
     1774816.494      569320.585     1774824.306      569199.491
     1774817.796      569001.574     1774815.192      568901.314
#Sta/Elev= 30
       0  682.74     9.3  681.26    18.7  679.02    46.7  671.56    65.3  667.19
    74.7   665.6    93.3   663.9   102.7   662.8     112  661.27   121.4  659.09
   130.8  655.24   140.2  650.24   149.6  646.26   159.1  646.23   168.5  647.24
   177.9  646.38   187.4  645.85   196.8   646.1   215.6   651.2   225.1  652.24
   234.5  652.32   300.5  651.56   309.9  652.71   319.4  656.47   355.8  677.82
   374.1  688.06   383.2  692.88   392.3  696.79   401.4  699.76   419.7  705.12
#Mann= 3 , 0 , 0
       0      .1       0   149.6    .045       0   177.9     .08       0
Bank Sta=149.6,177.9
XS Rating Curve= 0 ,0
Exp/Cntr=0.3,0.1

Type RM Length L Ch R = 1 ,14152.3 ,318.4,326.3,333.1
XS GIS Cut Line= 4
     1775135.504      569312.772     1775165.452      569219.022
     1775235.765      568979.439     1775192.796      568884.387
#Sta/Elev= 29
       0  687.56     9.8  683.85    19.7  680.44    29.5  676.94    39.4  673.22
    68.9  661.76    88.6  654.34    98.4  650.42     108   646.8   117.6  645.11
   127.2  645.46   136.8  647.64   146.4  649.48   165.6  650.02     204  650.89
   232.9  651.76   319.3  655.03   348.1  655.99   357.6   656.5   367.1  658.26
   376.6  662.08     386  666.58   395.5  670.47     405   673.5   414.5  676.33
     424  679.52   433.4  684.38   442.9  690.88   452.4  696.99
#Mann= 3 , 0 , 0
       0      .1       0     108    .045       0   136.8      .1       0
Bank Sta=108,136.8
XS Rating Curve= 0 ,0
Exp/Cntr=0.3,0.1

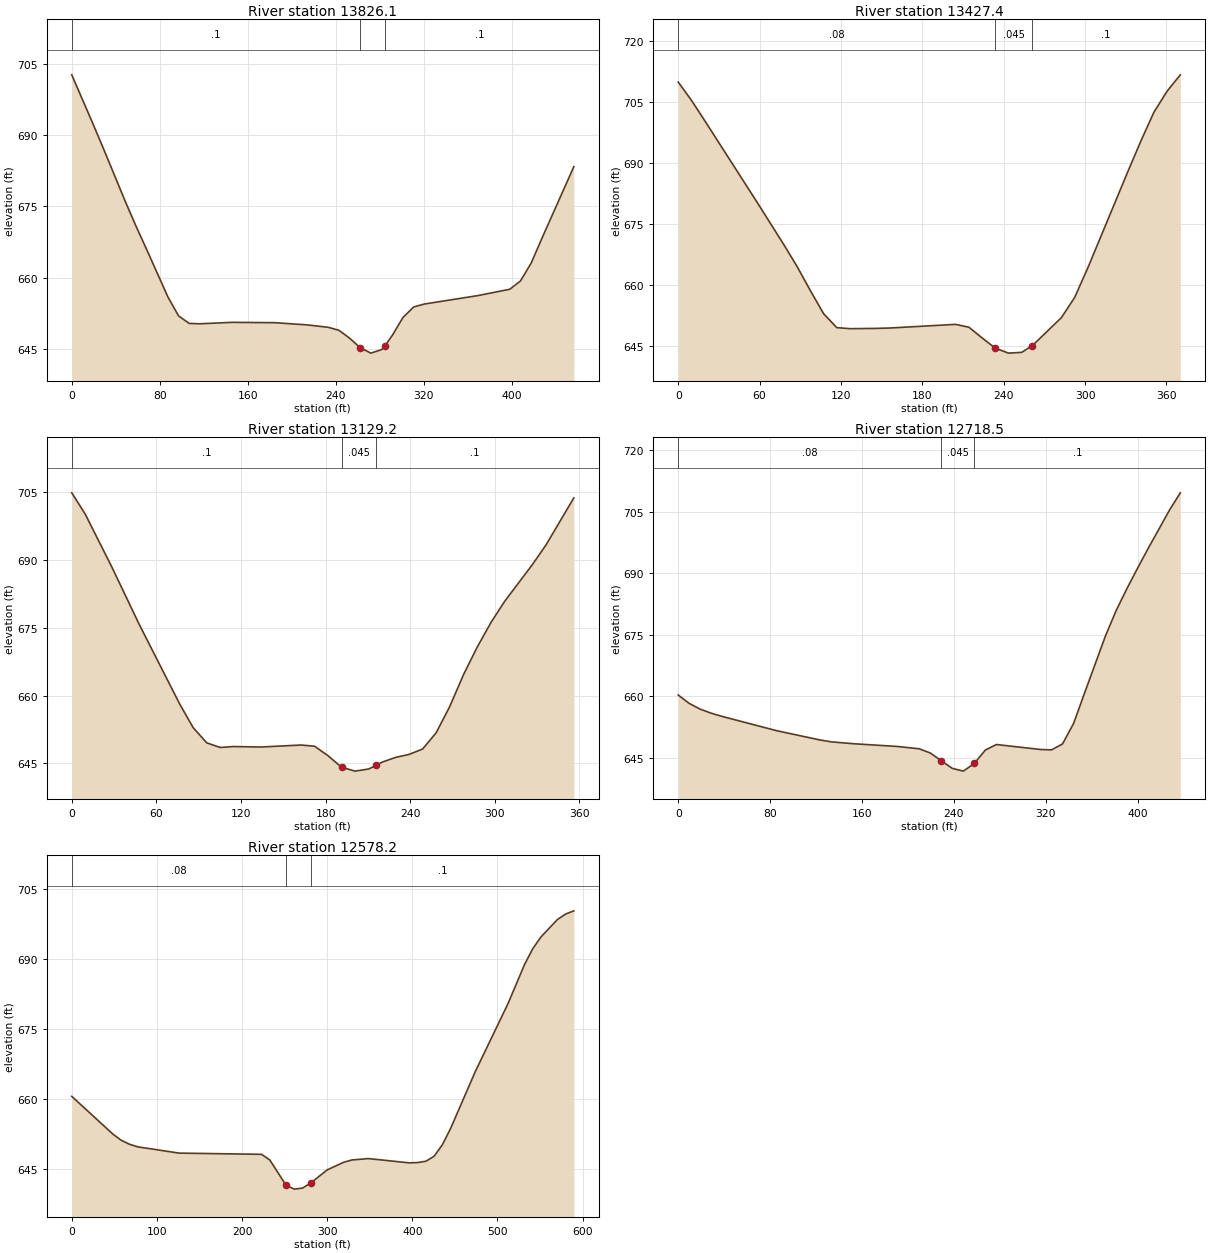
Type RM Length L Ch R = 1 ,13826.1 ,397.2,398.6,424.4
XS GIS Cut Line= 2
      1775351.65      569389.595     1775589.931      569000.272
#Sta/Elev= 30
       0  702.65    19.4  692.28    29.1  686.97    48.6  676.07    58.3  670.89
      68  665.98    87.4  655.96    97.1  651.97   106.8  650.39   116.5  650.32
   145.7  650.62   184.5  650.55   213.7  650.09   233.1  649.58   242.8  648.96
   252.5  647.31   262.2  645.29   271.9  644.15   281.6  644.88  284.77  645.71
   291.4  647.89   301.1  651.65   310.8  653.85   320.5  654.47     369  656.24
   398.2  657.58   407.9  659.32   417.6  663.07   427.3  668.24   456.4  683.35
#Mann= 3 , 0 , 0
       0      .1       0   262.2    .045       0  284.77      .1       0
Bank Sta=262.2,284.77
XS Rating Curve= 0 ,0
Exp/Cntr=0.3,0.1

Type RM Length L Ch R = 1 ,13427.4 ,297.7,298.3,298.7
XS GIS Cut Line= 2
      1775595.14       569554.96     1775828.212      569267.199
#Sta/Elev= 28
       0  709.82     9.7  705.36    19.5  700.36    58.5   680.1      78   669.8
    87.7  664.47    97.4   658.6   107.2   652.9   116.9  649.47   126.7  649.21
   146.2  649.28   155.9  649.37   204.6  650.27   214.4  649.56   224.1  646.94
   233.9  644.41   243.6   643.2   253.4  643.39  260.76     645   263.1  645.66
   282.6  651.92   292.4  656.89   302.1  664.16   331.3  687.57   341.1  695.24
   350.8  702.39   360.6   707.6   370.3   711.6
#Mann= 3 , 0 , 0
       0     .08       0   233.9    .045       0  260.76      .1       0
Bank Sta=233.9,260.76
XS Rating Curve= 0 ,0
Exp/Cntr=0.3,0.1

Type RM Length L Ch R = 1 ,13129.2 ,425.7,410.6,395.5
XS GIS Cut Line= 3
     1775808.681      569746.366     1775981.858      569541.939
     1776017.015       569461.21
#Sta/Elev= 30
       0  704.81     9.6  700.07    28.7  688.23    47.8  675.75    76.6  658.09
    86.1   652.9    95.7  649.55   105.2  648.53   114.8  648.73     134  648.63
   162.7  649.07   172.2   648.8   181.8  646.68   191.3  644.16   200.9   643.3
   210.5  643.77  215.77  644.55   220.1  645.29   229.6  646.33   239.2     647
   248.8  648.19   258.4  651.79   267.9   657.5   277.7  664.57   287.5  670.72
   297.3  676.19     307  680.85   326.6  688.94   336.4  693.36     356   703.7
#Mann= 3 , 0 , 0
       0      .1       0   191.3    .045       0  215.77      .1       0
Bank Sta=191.3,215.77
XS Rating Curve= 0 ,0
Exp/Cntr=0.3,0.1

Type RM Length L Ch R = 1 ,12718.5 ,131.1,140.3,150
XS GIS Cut Line= 4
      1776289.15      569893.501      1776326.91      569765.897
     1776334.723       569554.96     1776316.494      569463.814
#Sta/Elev= 30
       0  660.34     9.5   658.3      19  656.91    28.5  655.92      38  655.13
    85.6  651.64   123.6  649.36   133.1  648.92   152.3  648.46   190.6  647.79
   209.8  647.22   219.4   646.2     229   644.3   238.6  642.44   248.2  641.77
   257.8  643.65   267.4  646.92     277  648.26   315.4  647.05     325  646.95
   334.6  648.42   344.2   653.4   353.4  660.56     372  674.79   381.3  680.97
   390.6  686.28   399.9  691.28   409.2  696.14   427.8   705.5   437.1  709.66
#Mann= 3 , 0 , 0
       0     .08       0     229    .045       0   257.8      .1       0
Bank Sta=229,257.8
XS Rating Curve= 0 ,0
Exp/Cntr=0.3,0.1

Type RM Length L Ch R = 1 ,12578.2 ,96.9,104.3,107.8
XS GIS Cut Line= 3
     1776386.806      569889.595      1776438.89      569722.928
     1776596.442      569338.814
#Sta/Elev= 30
       0  660.56    48.5  652.45    58.2  651.15    67.9   650.3    77.6  649.75
   126.1  648.41   222.9  648.15   232.6  646.96   251.7  641.54   261.5   640.7
   271.2  640.93   280.8  642.03   300.1  644.82   319.4  646.45   329.1  646.94
   348.4  647.24   396.7  646.32   406.3  646.39     416  646.67   425.6  647.73
   435.3  650.18     445  653.67   473.9  665.81   512.5  680.43   531.9  688.79
   541.5  692.16   551.2  694.69   570.5  698.42   580.1  699.59   589.8  700.28
#Mann= 3 , 0 , 0
       0     .08       0   251.7    .045       0   280.8      .1       0
Bank Sta=251.7,280.8
XS Rating Curve= 0 ,0
Exp/Cntr=0.3,0.1