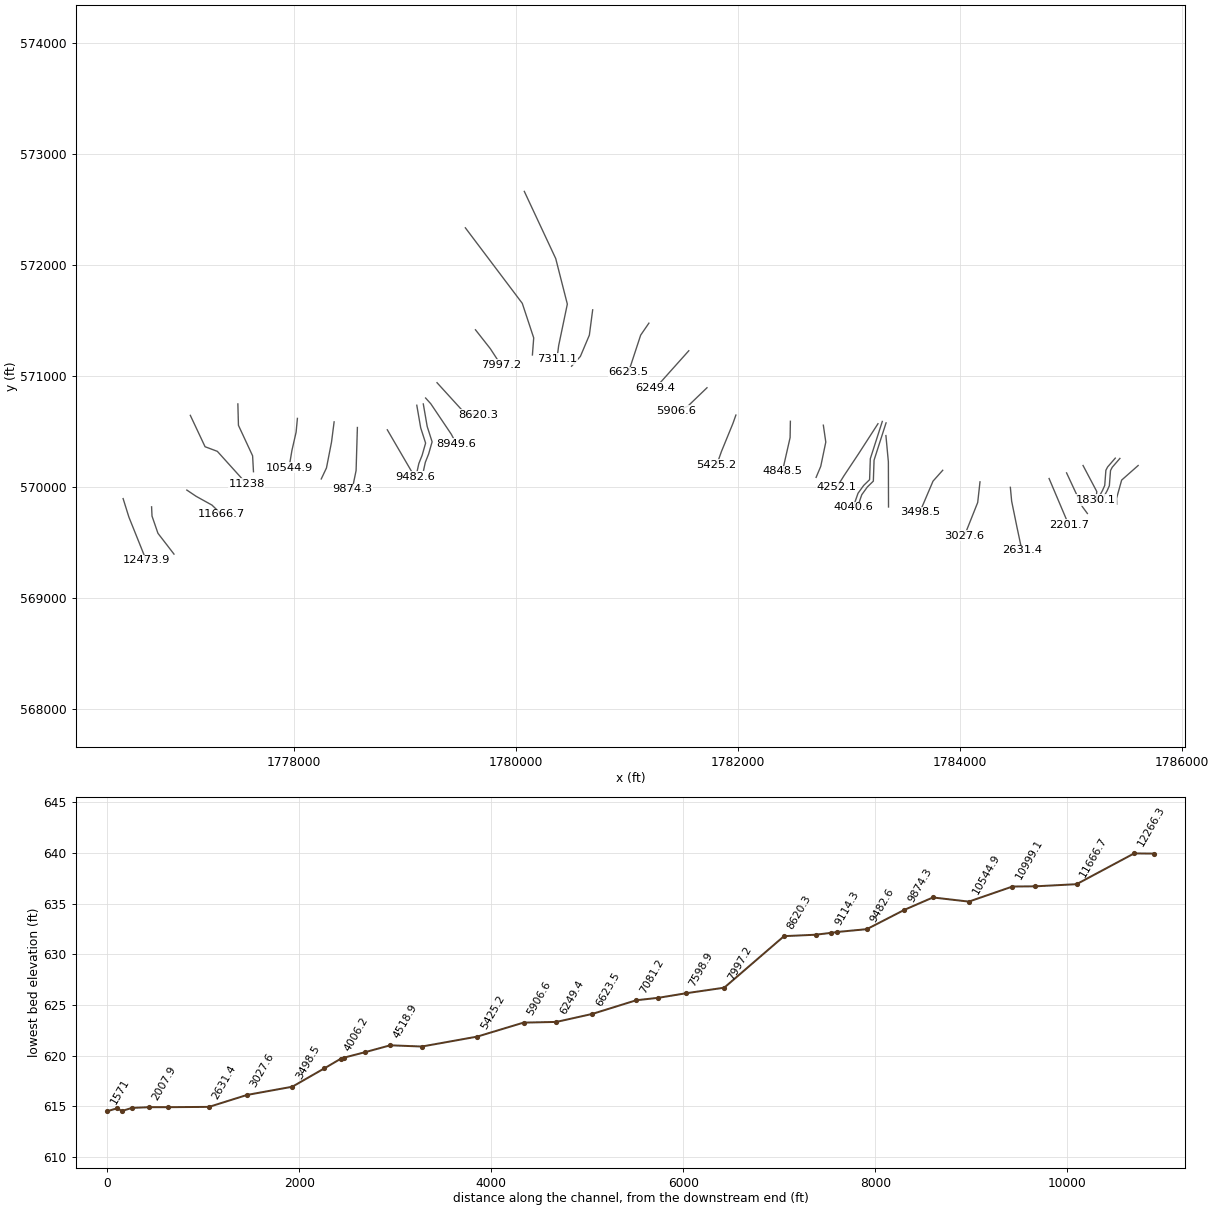
HEC-RAS study ALLENFK.prj: ALLENFK

--- ALLENFK.g01 (geometry) --- (continued)

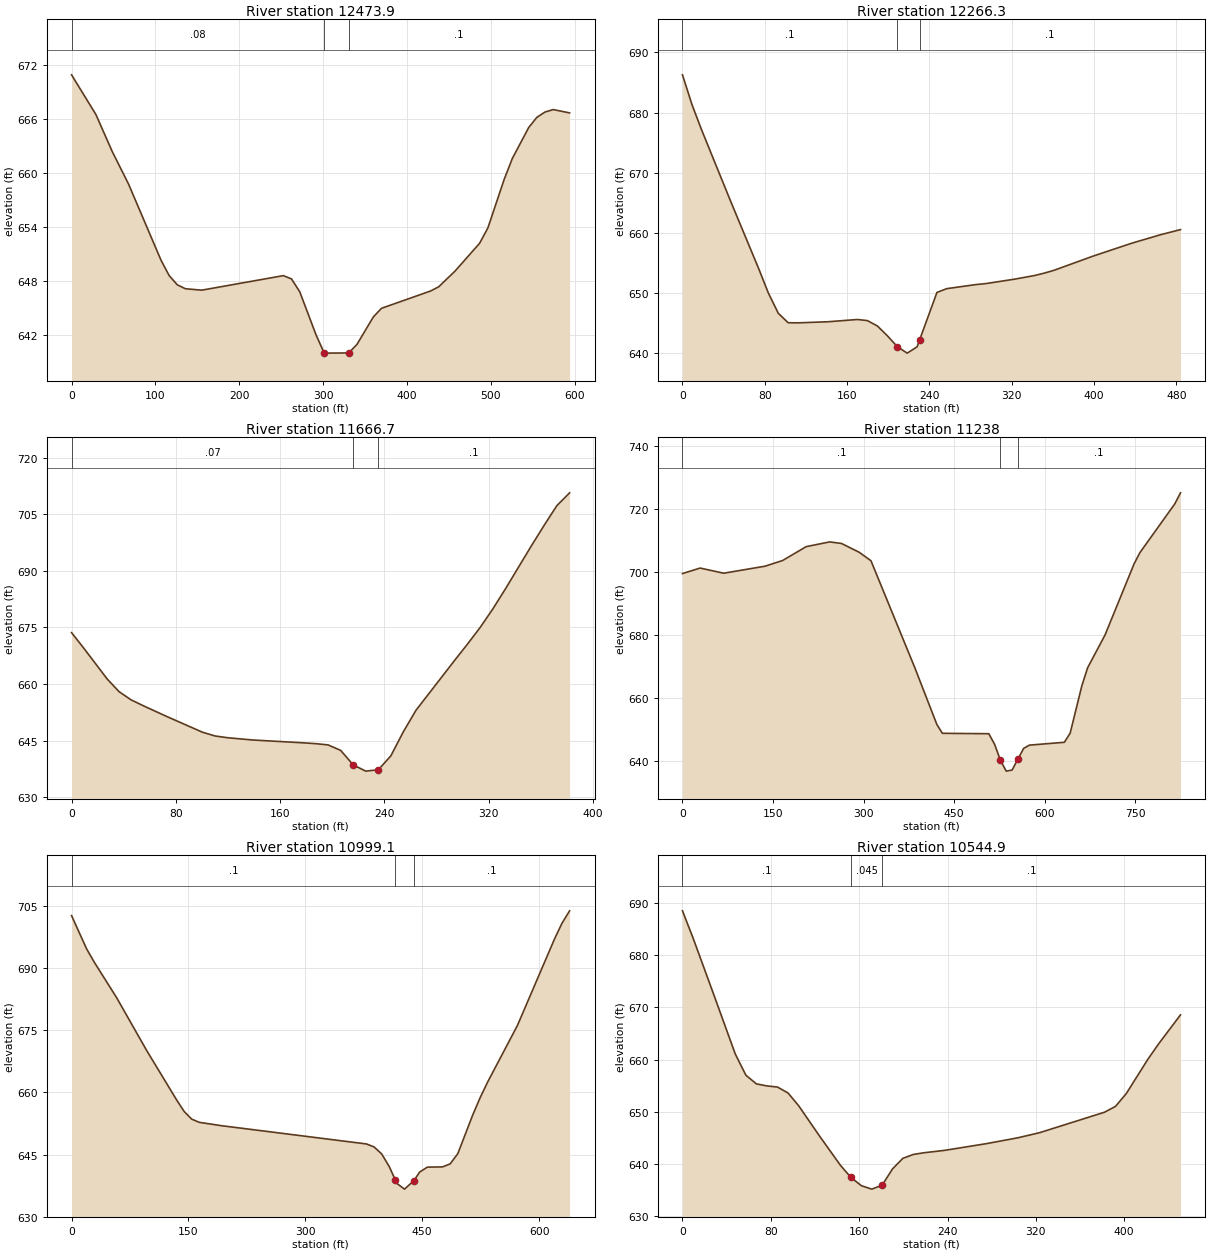
Type RM Length L Ch R = 1 ,12473.9 ,217.5,207.6,201.2
XS GIS Cut Line= 3
     1776463.629      569897.408     1776515.712      569730.741
     1776671.962      569341.418
#Sta/Elev= 30
       0  670.93    29.1   666.5    48.5  662.39    67.9  658.78   106.7  650.29
   116.4  648.58   126.1  647.55   135.8  647.11   155.2  646.95   252.7  648.57
   262.4   648.2   272.2  646.77   291.7  641.96   301.4  639.94   330.7  639.96
   340.5  640.92     360  643.97   369.7  644.93   428.3  646.86     438  647.33
   457.5  649.08   486.8  652.18   496.6  653.88   516.1   659.3   525.8  661.62
   545.3  665.06   555.1   666.2   564.8  666.79   574.6  667.06   594.1  666.69
#Mann= 3 , 0 , 0
       0     .08       0   301.4    .045       0   330.7      .1       0
Bank Sta=301.4,330.7
XS Rating Curve= 0 ,0
Exp/Cntr=0.3,0.1

Type RM Length L Ch R = 1 ,12266.3 ,582.6,599.6,616.3
XS GIS Cut Line= 4
      1776720.14      569823.189     1776724.046      569739.855
     1776777.431      569584.908     1776921.962      569397.408
#Sta/Elev= 30
       0  686.28     9.3   681.3    18.5  677.16    46.4  665.41    74.2  653.97
    83.4  649.99    93.1   646.6   102.7  645.02   112.4     645   141.3  645.18
   170.2  645.56   179.8  645.37   189.5  644.47   199.1  642.85   208.8  641.04
   218.4  639.96     228  641.01   230.5  642.18   247.3  650.06   256.8  650.69
   285.2  651.37   294.7  651.53   323.1  652.28     342  652.87   351.5  653.27
     361  653.74   398.8  656.09   436.7  658.26   465.1  659.69     484  660.52
#Mann= 3 , 0 , 0
       0      .1       0   208.8    .045       0   230.5      .1       0
Bank Sta=208.8,230.5
XS Rating Curve= 0 ,0
Exp/Cntr=0.3,0.1

Type RM Length L Ch R = 1 ,11666.7 ,437.6,428.7,419.6
XS GIS Cut Line= 4
     1777037.848       569974.23     1777121.181      569918.241
      1777264.41      569838.814     1777349.046      569756.783
#Sta/Elev= 30
       0  673.61     9.1  669.62    27.4   661.3    36.5  657.96    45.6  655.82
    54.8  654.28      73   651.4   100.4  647.23     110  646.24   119.7  645.77
   138.9  645.17   177.5  644.42   187.1   644.2   196.7  643.87   206.4  642.42
     216  638.59   225.6  636.92   235.3  637.28   244.9  640.97   254.5  647.36
   264.2  653.06   293.6  666.17   303.5   670.5   313.3  674.94   323.1  679.89
   332.9  685.28   352.6  696.57   362.4  702.01   372.2  707.25     382  710.66
#Mann= 3 , 0 , 0
       0     .07       0     216    .045       0   235.3      .1       0
Bank Sta=216,235.3
XS Rating Curve= 0 ,0
Exp/Cntr=0.3,0.1

Type RM Length L Ch R = 1 ,11238   ,245.8,238.9,232.1
XS GIS Cut Line= 4
     1777069.098      570647.408      1777201.91      570364.855
     1777312.587      570323.189      1777576.91       570030.22
#Sta/Elev= 30
       0   699.4    29.3  701.15    68.3  699.51   136.6  701.73   165.9  703.54
   204.9  707.94   243.9  709.45   263.4  708.95   292.7  706.16   312.2  703.48
     385  669.47   421.4  651.52   430.5  648.71   507.5  648.58   517.1  645.19
   526.7  640.14   536.3  636.71     546  637.05   555.6   640.5   565.2  643.94
   574.8  644.96   632.6  645.86   642.2  648.75   661.4  663.68   671.1   669.5
   699.9  679.88   748.1  702.48   757.7  706.03   815.4  721.48     825  725.02
#Mann= 3 , 0 , 0
       0      .1       0   526.7    .045       0   555.6      .1       0
Bank Sta=526.7,555.6
XS Rating Curve= 0 ,0
Exp/Cntr=0.3,0.1

Type RM Length L Ch R = 1 ,10999.1 ,469.5,454.2,438.3
XS GIS Cut Line= 4
     1777497.483      570750.272     1777502.692      570557.564
     1777630.296      570282.824     1777638.108      570139.595
#Sta/Elev= 30
       0  702.62    19.3  694.61    28.9  691.46    57.8  682.85    96.4   670.1
     135  658.14   144.6  655.39   154.2  653.56   163.9  652.79   192.8  651.97
   378.4  647.58   388.2  646.87     398  645.18   407.8   642.1  415.26  639.01
   417.5  638.07   427.3  636.69  439.44  638.76   446.8  640.81   456.6  641.99
   476.2  642.05   485.9  642.78   495.7  645.24   514.8  654.53   524.4  658.74
     534   662.5   572.2  676.12     620  697.06   629.6  700.84   639.2  703.77
#Mann= 3 , 0 , 0
       0      .1       0  415.26    .045       0  439.44      .1       0
Bank Sta=415.26,439.44
XS Rating Curve= 0 ,0
Exp/Cntr=0.3,0.1

Type RM Length L Ch R = 1 ,10544.9 ,372.9,374.4,375
XS GIS Cut Line= 4
     1778033.942      570620.064     1778022.223      570496.366
     1777984.462      570331.001     1777958.421      570176.053
#Sta/Elev= 30
       0  688.49     9.6  683.28    28.7  672.24    47.8  661.08    57.4  657.02
    66.9  655.36    76.5  654.96      86  654.75    95.6  653.61   105.1   651.2
   124.2  645.34   143.1  639.75   152.5  637.44     162  635.86   171.4   635.2
   180.8  635.95   190.2  639.07   199.6   641.1   209.1  641.84   218.5  642.16
   237.3  642.62     275   643.9   303.7  645.03   323.3     646   382.2  649.93
   392.1  651.04   401.9   653.5   421.5  660.08   431.4  663.08     451  668.57
#Mann= 3 , 0 , 0
       0      .1       0   152.5    .045       0   180.8      .1       0
Bank Sta=152.5,180.8
XS Rating Curve= 0 ,0
Exp/Cntr=0.3,0.1

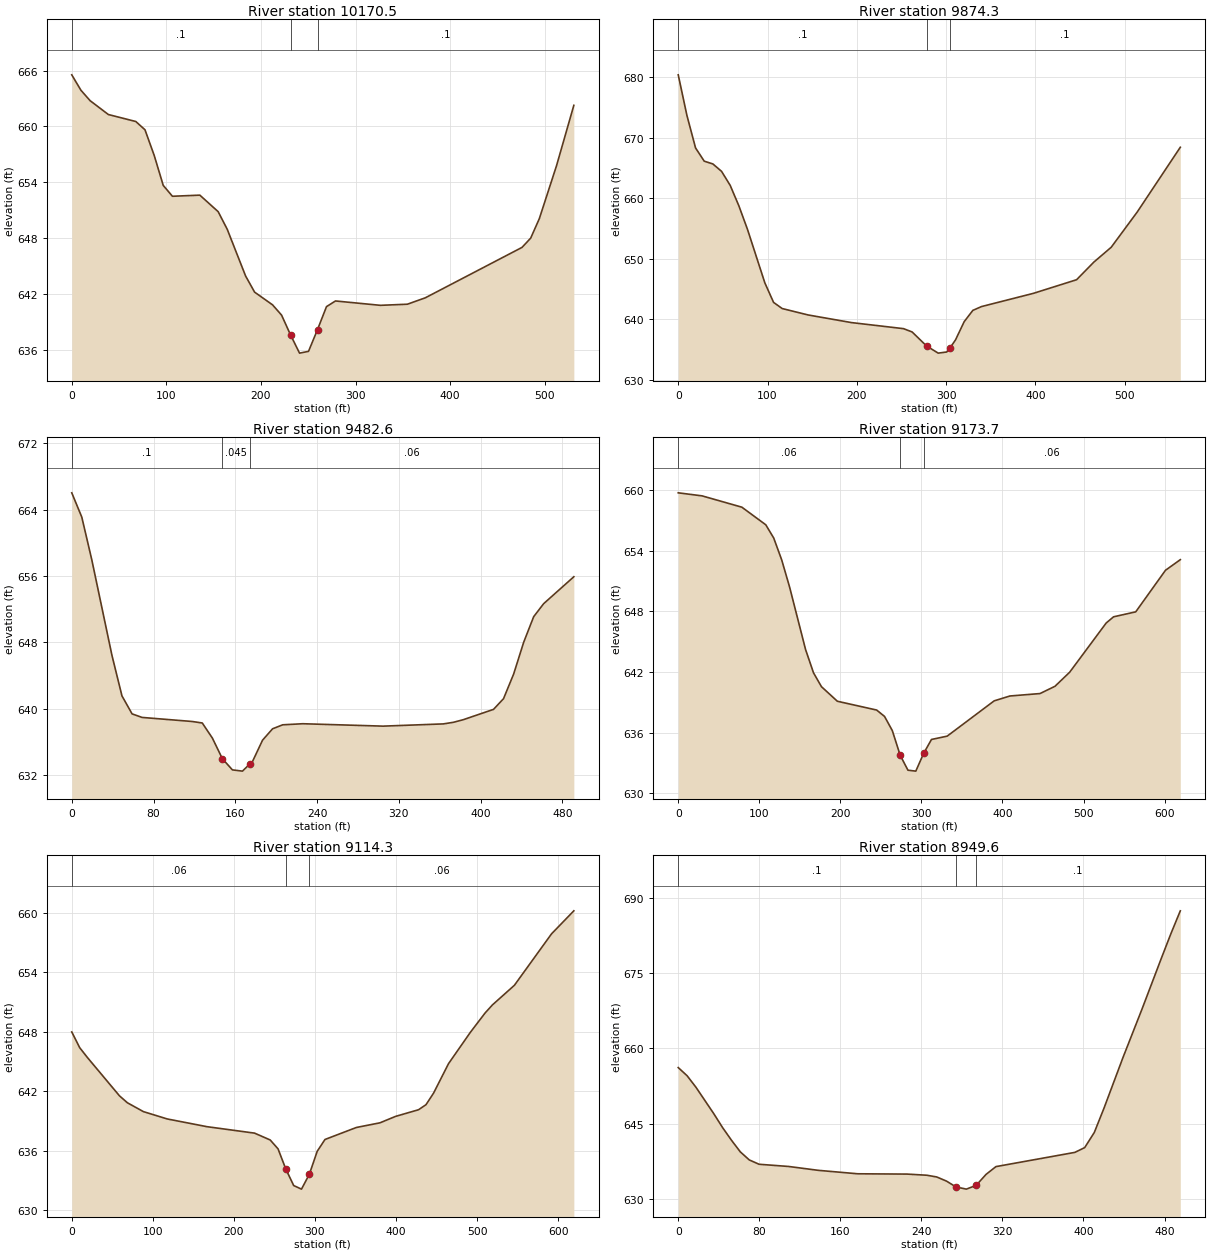
Type RM Length L Ch R = 1 ,10170.5 ,293.9,296.2,305.7
XS GIS Cut Line= 4
     1778364.671      570588.814     1778341.233      570406.522
      1778295.66      570173.449     1778248.785      570074.491
#Sta/Elev= 30
       0  665.54     9.7  663.88    19.4  662.76    38.7  661.27    67.7  660.52
    77.4  659.63    87.1  656.89    96.7  653.65   106.4  652.48   135.4   652.6
   154.8  650.82   164.4  648.92   183.8   643.9   193.3  642.17   212.3   640.8
   221.8   639.7   231.3  637.57   240.8  635.61   250.3   635.8   259.8  638.14
   269.3  640.61   278.8  641.22   326.3  640.75   354.8  640.87   373.8  641.56
     476  646.98   485.2  647.98   494.3  650.07   512.5  655.77   530.8  662.26
#Mann= 3 , 0 , 0
       0      .1       0   231.3    .045       0   259.8      .1       0
Bank Sta=231.3,259.8
XS Rating Curve= 0 ,0
Exp/Cntr=0.3,0.1

Type RM Length L Ch R = 1 ,9874.3  ,376.2,391.7,407.1
XS GIS Cut Line= 3
     1778574.306      570538.033     1778562.587      570150.012
     1778527.431      569979.439
#Sta/Elev= 30
       0  680.42     9.7  673.72    19.4  668.33    29.1  666.14    38.8  665.68
    48.5  664.46    58.2  662.14    67.9  658.76    77.6  654.85      97  646.02
   106.8  642.78   116.5  641.76   145.6   640.7   194.1  639.44   252.3  638.44
     262  637.89   278.1  635.58   291.2  634.39   300.8  634.58  304.52  635.28
   310.6  636.58   320.3  639.59     330  641.46   339.7  642.09   397.9  644.28
   446.2  646.53   465.6  649.45     485   651.9     514   657.7   562.4  668.44
#Mann= 3 , 0 , 0
       0      .1       0   278.1    .045       0  304.52      .1       0
Bank Sta=278.1,304.52
XS Rating Curve= 0 ,0
Exp/Cntr=0.3,0.1

Type RM Length L Ch R = 1 ,9482.6  ,317.8,308.9,293.2
XS GIS Cut Line= 2
     1778843.837      570517.199     1779091.233       570092.72
#Sta/Elev= 30
       0  666.01     9.8  663.09    19.6  657.94    39.3  646.44    49.1  641.55
      59  639.38    68.8  638.95   117.9  638.46   127.7  638.28   137.6  636.46
   147.4  633.97   157.2  632.63     167  632.48   174.5  633.37   176.9  633.65
   186.7  636.21   196.5  637.58   206.4  638.06     226  638.19   304.6   637.9
   363.6  638.17   373.4  638.36   383.2  638.68   412.7  639.92   422.5  641.21
   432.4  644.18   442.2     648     452  651.09   461.8  652.66   491.3   655.9
#Mann= 3 , 0 , 0
       0      .1       0   147.4    .045       0   174.5     .06       0
Bank Sta=147.4,174.5
XS Rating Curve= 0 ,0
Exp/Cntr=0.3,0.1

Type RM Length L Ch R = 1 ,9173.7  ,59.4,59.4,59.4
XS GIS Cut Line= 6
     1779109.462      570738.553     1779144.619      570535.428
      1779188.89      570397.408      1779157.64      570288.033
     1779127.692      570212.512     1779112.067      570140.897
#Sta/Elev= 30
       0  659.72    29.4  659.42    78.5   658.3     108  656.56   117.8  655.25
   127.6   653.1   137.4   650.4   157.1  644.22   166.9  641.92   176.7  640.55
   196.3  639.11   244.8  638.24   254.5  637.61   264.1  636.21   273.8  633.77
   283.4  632.29   293.1   632.2   302.8  633.96   312.4  635.33   331.8  635.66
   389.8  639.15   409.2  639.63   446.3  639.87   464.8  640.59   482.9  641.98
     528  646.85   537.1  647.46   564.4  647.95   601.1  652.06   619.4  653.11
#Mann= 3 , 0 , 0
       0     .06       0   273.8    .045       0   302.8     .06       0
Bank Sta=273.8,302.8
XS Rating Curve= 0 ,0
Exp/Cntr=0.3,0.1

Type RM Length L Ch R = 1 ,9114.3  ,159.2,164.7,170.9
XS GIS Cut Line= 6
     1779168.056      570750.272     1779203.212      570547.147
     1779247.483      570409.126     1779216.233      570299.751
     1779186.285       570224.23      1779170.66      570152.616
#Sta/Elev= 30
       0  647.98     9.8  646.39    19.6  645.37    58.9  641.53    68.7  640.83
    88.4  639.94   117.8   639.2   166.9  638.42   225.5  637.77   244.8  637.08
   254.5  636.18   264.1  634.14   273.8  632.48   283.4  632.12   293.1  633.62
   302.8  635.94   312.4  637.13   351.1  638.34   380.2  638.81   399.5  639.46
   427.8  640.13     437  640.64   446.3   641.8   464.8  644.78   491.9  647.96
     510   649.9     519  650.71   546.1  652.69   591.9  657.88   619.4   660.2
#Mann= 3 , 0 , 0
       0     .06       0   264.1    .045       0   293.1     .06       0
Bank Sta=264.1,293.1
XS Rating Curve= 0 ,0
Exp/Cntr=0.3,0.1

Type RM Length L Ch R = 1 ,8949.6  ,324.6,329.3,332.2
XS GIS Cut Line= 4
      1779188.89      570803.658     1779235.765      570751.574
      1779420.66      570476.835     1779464.931      570393.501
#Sta/Elev= 30
       0  656.18     8.8  654.54    17.5  652.25      35  647.01    43.8   644.2
    52.6  641.67    61.3  639.36    70.1  637.76    79.8  636.89     109  636.45
   138.2  635.68   177.2  634.99   225.9  634.93   245.4   634.7   255.1  634.36
   264.9  633.52   274.1  632.37   284.4  631.93   294.1  632.68   303.8  634.86
   313.6  636.42   391.5  639.26   401.2  640.21   410.7  643.23   420.1  647.99
     439  658.18   457.8  667.85   476.7  677.89   486.2  682.83   495.6  687.45
#Mann= 3 , 0 , 0
       0      .1       0   274.1    .045       0   294.1      .1       0
Bank Sta=274.1,294.1
XS Rating Curve= 0 ,0
Exp/Cntr=0.3,0.1

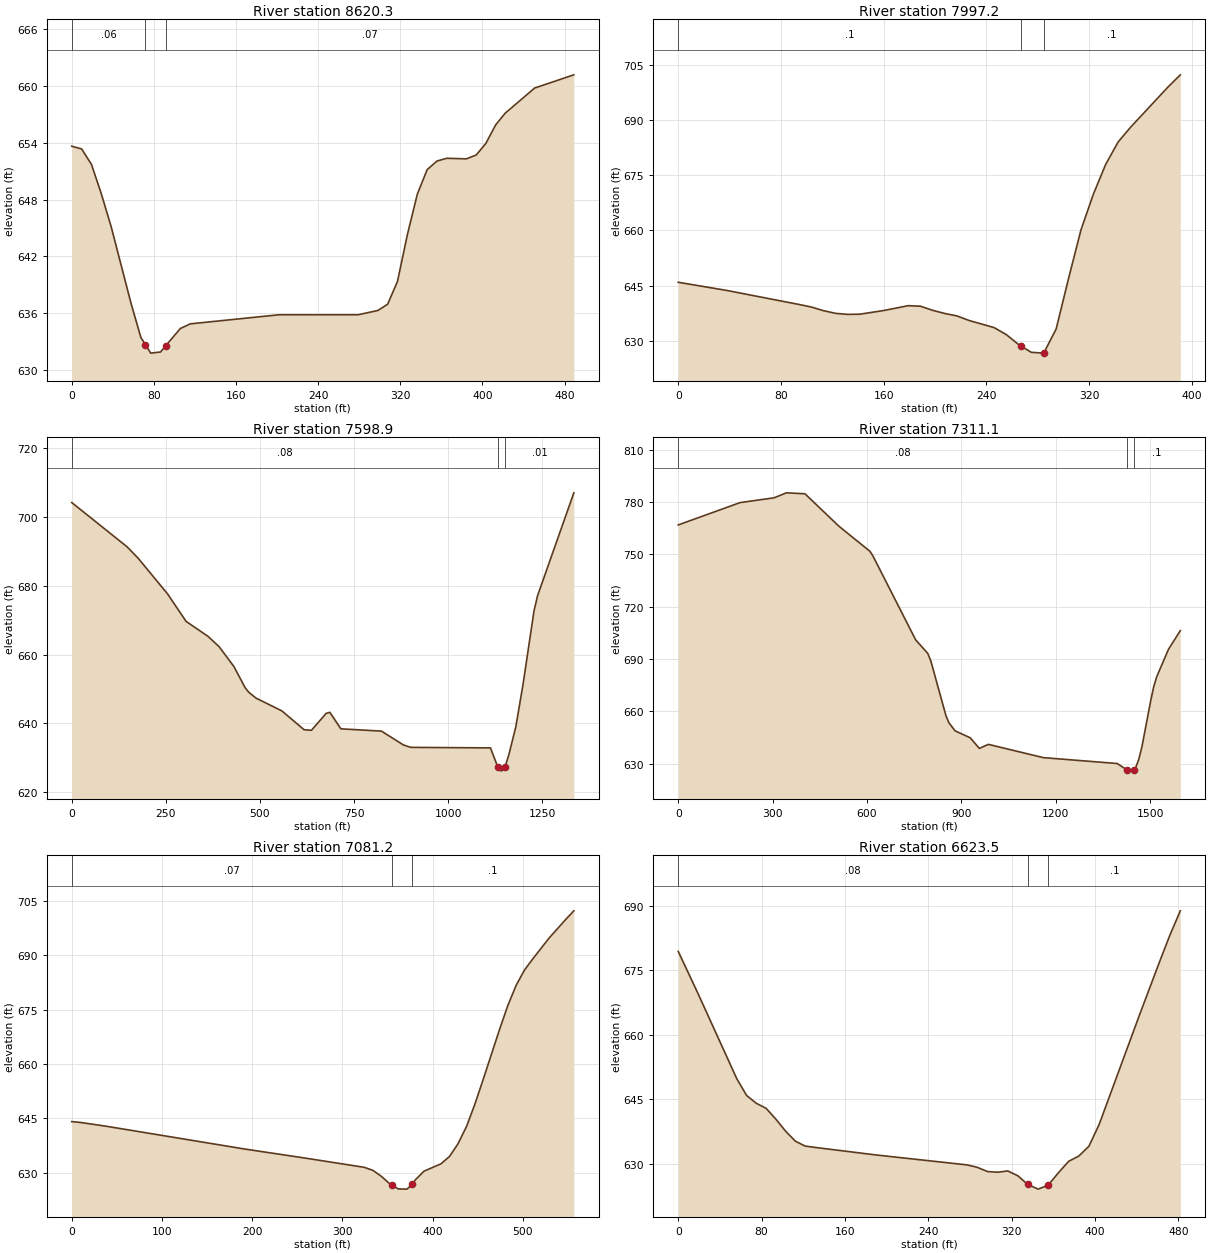
Type RM Length L Ch R = 1 ,8620.3  ,625.2,623.1,621
XS GIS Cut Line= 3
     1779291.754      570941.678     1779531.337      570678.658
     1779661.546      570650.012
#Sta/Elev= 30
       0  653.63     9.6  653.35    19.2  651.71    28.8  648.61    38.5  645.09
    57.7  637.06    67.3  633.45    71.7  632.69    76.9  631.79    86.5  631.91
   91.67  632.59   105.8  634.39   115.4  634.88   201.9  635.84   278.9  635.84
   298.1  636.29   307.7  636.95   317.3  639.36   326.9  644.28   336.6  648.56
   346.2  651.16   355.8  652.07   365.3  652.36   384.4   652.3   393.9   652.7
   403.4  653.93   412.9  655.88   422.4  657.14     451  659.78   489.1  661.17
#Mann= 3 , 0 , 0
       0     .06       0    71.7    .045       0   91.67     .07       0
Bank Sta=71.7,91.67
XS Rating Curve= 0 ,0
Exp/Cntr=0.3,0.1

Type RM Length L Ch R = 1 ,7997.2  ,404.1,398.3,392.5
XS GIS Cut Line= 3
     1779638.108      571418.241     1779772.223      571247.668
     1779867.275      571101.835
#Sta/Elev= 30
       0  645.94    37.7  643.73    94.3   639.9   103.8  639.21   113.2  638.22
   122.6   637.5   132.1  637.22   141.5  637.27   160.4  638.29   179.2  639.59
   188.7  639.44   198.1  638.33   207.6  637.47     217  636.81   226.6  635.56
     246  633.64   255.7   631.7   265.3  628.98   267.1   628.6     275  626.92
   284.7   626.7   294.4  633.27     304  646.91   313.7  660.13   323.4  669.88
     333  677.98   342.7  684.05   352.4  688.06   381.4  698.92   391.1  702.27
#Mann= 3 , 0 , 0
       0      .1       0   267.1    .045       0   284.7      .1       0
Bank Sta=267.1,284.7
XS Rating Curve= 0 ,0
Exp/Cntr=0.3,0.1

Type RM Length L Ch R = 1 ,7598.9  ,298,287.7,276.6
XS GIS Cut Line= 4
     1779546.893       572337.06     1780059.983      571656.522
     1780162.848      571345.324     1780151.129      571191.678
#Sta/Elev= 30
       0   704.2     147  691.34   176.3  688.04   254.7  677.64   303.7  669.68
   362.5  665.28   391.9  662.27     431  656.52   460.4  650.44   470.2  649.08
   489.8  647.36   558.4  643.65   617.2  638.19   636.8  638.01     676  642.94
   685.8  643.24   715.1  638.44   822.9  637.78   881.2  633.76   900.5  633.06
  1112.6   632.9  1131.8  627.42  1141.5  626.15  1151.1  627.32  1160.8  630.66
    1180  639.07  1199.3   651.5  1228.2  672.67  1237.8  677.16  1334.1  707.03
#Mann= 3 , 0 , 0
       0     .08       0  1131.8    .045       0  1151.1     .01       0
Bank Sta=1131.8,1151.1
XS Rating Curve= 0 ,0
Exp/Cntr=0.3,0.1

Type RM Length L Ch R = 1 ,7311.1  ,235.5,229.9,225.2
XS GIS Cut Line= 5
     1780078.143      572665.185     1780361.132      572060.134
     1780465.799      571649.578     1780387.674       571275.88
     1780372.049      571154.786
#Sta/Elev= 30
       0  766.95   196.5  779.76   304.5   782.5   343.8  785.37   402.7  784.82
   510.8  766.19     609  751.86   618.8  749.14   754.6  700.98   793.1  693.23
   802.8  688.84   850.9  657.43   860.5  653.36   879.8  648.81     928  644.82
   956.8  638.74   985.7  641.05  1160.2  633.44  1395.1  630.06  1424.5  626.57
  1434.3   625.7  1447.8  626.54  1453.8  627.79  1463.6  632.54  1473.4  639.56
  1501.6  666.24    1511  674.13  1520.4   679.8    1558  695.61  1595.5   706.3
#Mann= 3 , 0 , 0
       0     .08       0  1424.5    .045       0  1447.8      .1       0
Bank Sta=1424.5,1447.8
XS Rating Curve= 0 ,0
Exp/Cntr=0.3,0.1

Type RM Length L Ch R = 1 ,7081.2  ,455.6,457.7,459.4
XS GIS Cut Line= 4
     1780694.098      571597.928      1780664.15      571370.064
     1780583.421      571178.658     1780503.994      571090.116
#Sta/Elev= 29
       0   644.1     9.6  643.87    38.3  642.82   191.5  636.54   258.2  634.05
   324.2  631.48   333.7  630.65   343.1  629.01   352.6   626.9   355.2  626.52
     362  625.51   371.5  625.46  377.33  626.76   380.9  628.04   390.4  630.41
   409.2  632.45   418.7  634.48   428.1  637.98   437.6  642.78   446.7  648.85
   455.9  655.66   474.2  669.57   483.3  676.14   492.5   681.7   501.6  685.87
   510.8  688.97   529.1  694.79   547.4  699.89   556.5   702.3
#Mann= 3 , 0 , 0
       0     .07       0   355.2    .045       0  377.33      .1       0
Bank Sta=355.2,377.33
XS Rating Curve= 0 ,0
Exp/Cntr=0.3,0.1

Type RM Length L Ch R = 1 ,6623.5  ,384.2,374.1,361.7
XS GIS Cut Line= 3
     1781200.608      571478.137      1781126.39      571370.064
     1781017.015       571036.73
#Sta/Elev= 30
       0  679.37    18.7  669.72    56.2  649.78    65.6  645.89    74.9  644.07
    84.3   642.9    93.6  640.41     103   637.6   112.4  635.26   121.7  634.13
   131.1  633.81   189.6  632.06   277.3  629.74     287  629.18   296.8   628.2
   306.5  628.03   316.3  628.34     326  627.21   335.4  625.21   345.5  624.11
   355.2  625.06     365  627.94   374.7  630.57   384.5   631.8   394.2  634.09
     404  639.14   442.9  664.71   462.4  677.22   472.2  683.32   481.9   688.8
#Mann= 3 , 0 , 0
       0     .08       0   335.4    .045       0   355.2      .1       0
Bank Sta=335.4,355.2
XS Rating Curve= 0 ,0
Exp/Cntr=0.3,0.1

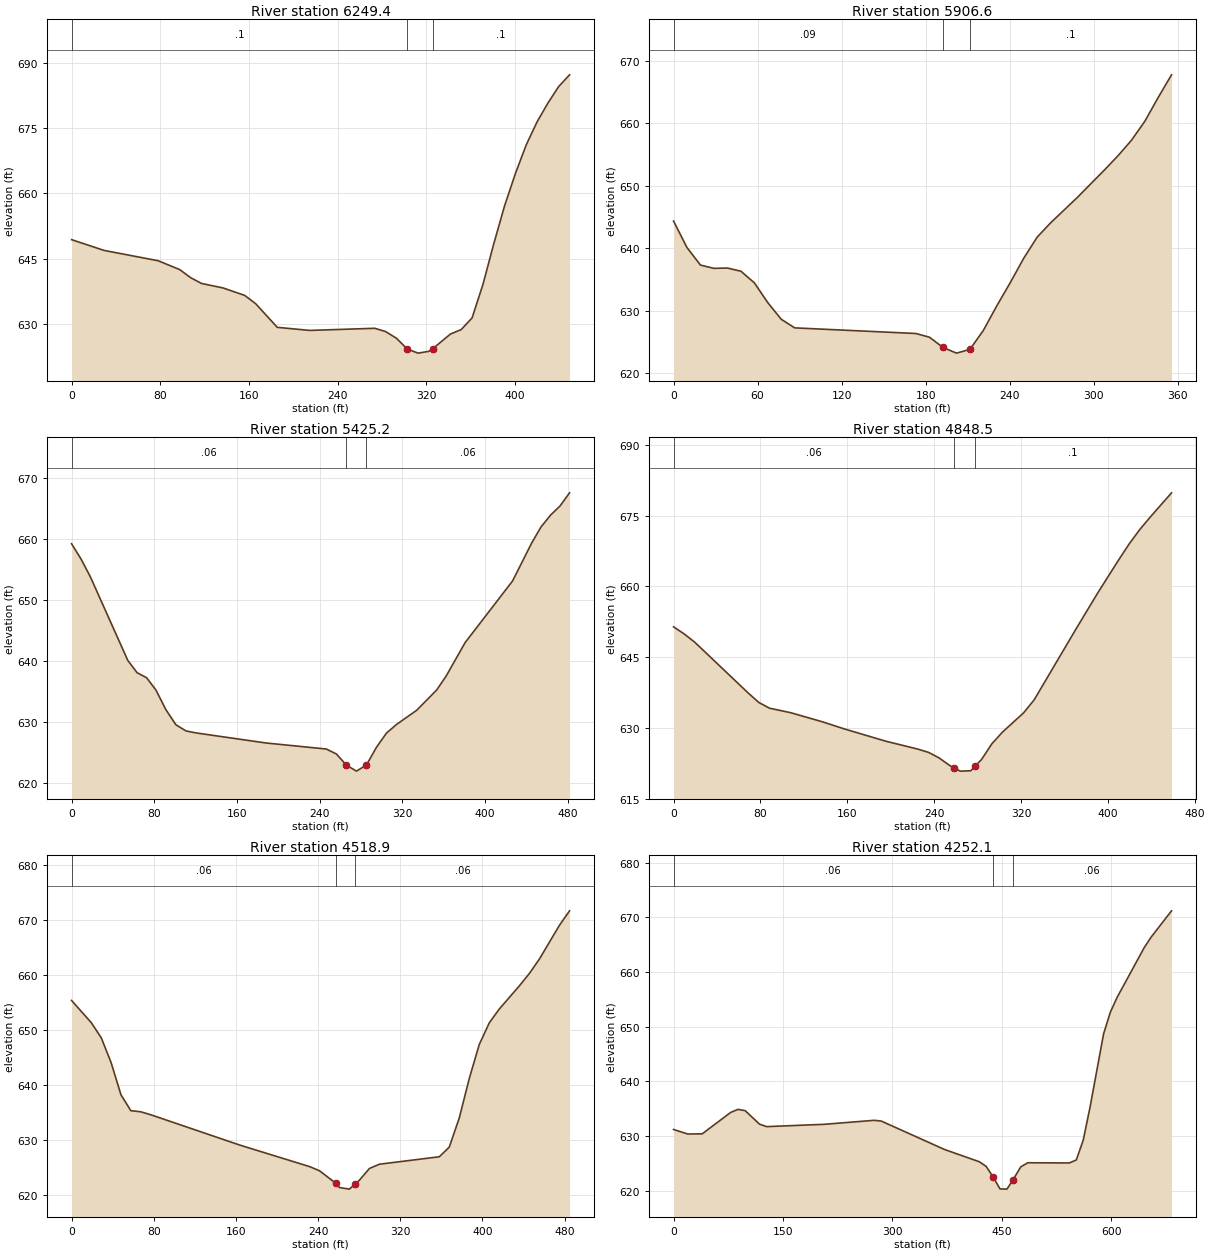
Type RM Length L Ch R = 1 ,6249.4  ,344.7,342.8,341.5
XS GIS Cut Line= 2
     1781559.983      571229.439     1781260.504      570894.803
#Sta/Elev= 30
       0  649.36    29.3  646.89    78.1  644.52    97.6  642.48   107.4  640.63
   117.2  639.31   136.7  638.27   156.2  636.56     166  634.67   185.5  629.24
   214.8  628.53   273.4  629.02   283.1  628.28   292.9  626.75   302.6   624.3
   312.4  623.32   322.2  623.73  325.51  624.29   341.7   627.7   351.4  628.72
   361.2   631.4     371  639.08   380.7  648.35   390.5  657.12   400.3  664.55
     410  671.08   419.8  676.38   429.6   680.7   439.3  684.49   449.1  687.18
#Mann= 3 , 0 , 0
       0      .1       0   302.6    .045       0  325.51      .1       0
Bank Sta=302.6,325.51
XS Rating Curve= 0 ,0
Exp/Cntr=0.3,0.1

Type RM Length L Ch R = 1 ,5906.6  ,471.6,481.3,490
XS GIS Cut Line= 3
     1781724.046      570896.105     1781550.869      570729.439
     1781444.098       570686.47
#Sta/Elev= 28
       0  644.38     9.6  640.14    19.2  637.34    28.8  636.81    38.5  636.86
    48.1  636.35    57.7  634.49    67.3  631.32    76.9  628.66    86.5  627.29
     173  626.39   182.7  625.79   192.3  624.16   201.9  623.25   211.5  623.84
   221.1  626.88   230.7  630.81   240.4  634.56   249.9  638.42   259.5   641.8
   269.1  644.09   288.3  648.18   307.5  652.54   317.1   654.8   326.7  657.27
   336.3  660.32   345.8  664.11   355.4  667.77
#Mann= 3 , 0 , 0
       0     .09       0   192.3    .045       0   211.5      .1       0
Bank Sta=192.3,211.5
XS Rating Curve= 0 ,0
Exp/Cntr=0.3,0.1

Type RM Length L Ch R = 1 ,5425.2  ,573.4,576.7,580.5
XS GIS Cut Line= 4
     1781984.462      570650.012     1781957.119      570573.189
     1781854.254      570321.887     1781811.285      570200.793
#Sta/Elev= 30
       0  659.23     9.1  656.74    18.1  653.83    54.4  640.06    63.4  638.04
    72.5  637.23    81.5  635.22    91.2  631.98   100.9  629.49   110.6  628.48
   120.3  628.15   188.2  626.49   246.4   625.5   256.1  624.69   265.8  622.85
   275.5  621.87   285.2  622.87   294.9   625.8   304.6  628.13   314.3  629.54
   333.7  631.86   353.1   635.2   362.3   637.5   380.6  642.99   426.5  653.12
   444.9  659.33     454  661.99   463.2  663.93   472.4  665.44   481.6   667.6
#Mann= 3 , 0 , 0
       0     .06       0   265.8    .045       0   285.2     .06       0
Bank Sta=265.8,285.2
XS Rating Curve= 0 ,0
Exp/Cntr=0.3,0.1

Type RM Length L Ch R = 1 ,4848.5  ,329,329.7,330.2
XS GIS Cut Line= 3
     1782475.348      570594.022     1782472.744      570446.887
     1782403.733      570143.501
#Sta/Elev= 30
       0  651.45     9.8  649.95    19.6  648.18    68.7  637.44    78.5  635.43
    88.3  634.22   107.9  633.26   137.4  631.31   156.9  629.85   195.8   627.2
   224.9  625.55   234.7  624.86   244.4  623.69   254.1  622.09   257.7  621.64
   263.8  620.89   273.6  620.96  277.24  621.91   283.3   623.3     293  626.69
   302.7  629.15   322.2  633.24   331.9  635.99   370.8  651.15   390.2  658.55
   409.7  665.64   419.4  669.03   429.1  672.06   438.8  674.72   458.3  679.83
#Mann= 3 , 0 , 0
       0     .06       0   257.7    .045       0  277.24      .1       0
Bank Sta=257.7,277.24
XS Rating Curve= 0 ,0
Exp/Cntr=0.3,0.1

Type RM Length L Ch R = 1 ,4518.9  ,275.4,266.8,258.2
XS GIS Cut Line= 4
     1782772.223      570558.866     1782794.358      570406.522
     1782748.785      570187.772     1782707.119      570088.814
#Sta/Elev= 30
       0  655.34    19.2   651.3    28.9  648.55    38.5  644.03    48.1  638.18
    57.7  635.28    67.4  635.08      77  634.55   163.7  629.03   231.7  625.11
   241.4  624.35  257.31  622.07   260.8   621.3   270.5  621.01   276.3  621.98
   280.2  622.63     290  624.77   299.7  625.54     358   626.9   367.7  628.65
   377.4  633.93   387.2  641.15   396.9  647.32   406.7  651.28   416.4  653.78
     436  658.01   445.7  660.25   455.5  662.89     475  669.03   484.8  671.65
#Mann= 3 , 0 , 0
       0     .06       0  257.31    .045       0   276.3     .06       0
Bank Sta=257.31,276.3
XS Rating Curve= 0 ,0
Exp/Cntr=0.3,0.1

Type RM Length L Ch R = 1 ,4252.1  ,206.6,211.5,206.6
XS GIS Cut Line= 4
      1783264.41      570571.887     1783088.629      570299.751
     1782957.119      570101.835     1782893.317       569998.97
#Sta/Elev= 30
       0  631.22    19.6  630.39    39.3  630.42    78.5  634.35    88.4  634.89
    98.2  634.66   117.8   632.2   127.6  631.74   206.2  632.16   274.9  632.89
   284.7  632.76   371.5  627.56     419  625.33   428.5  624.48     438  622.56
   447.5  620.36     457  620.32   465.1  621.97     476  624.39   485.6  625.14
   542.6   625.1   552.1  625.65   561.6  629.28   570.9  635.28   589.5   648.7
   598.8  652.67   608.2   655.4   645.4   664.5   654.7  666.37   682.6  671.17
#Mann= 3 , 0 , 0
       0     .06       0     438    .045       0   465.1     .06       0
Bank Sta=438,465.1
XS Rating Curve= 0 ,0
Exp/Cntr=0.3,0.1

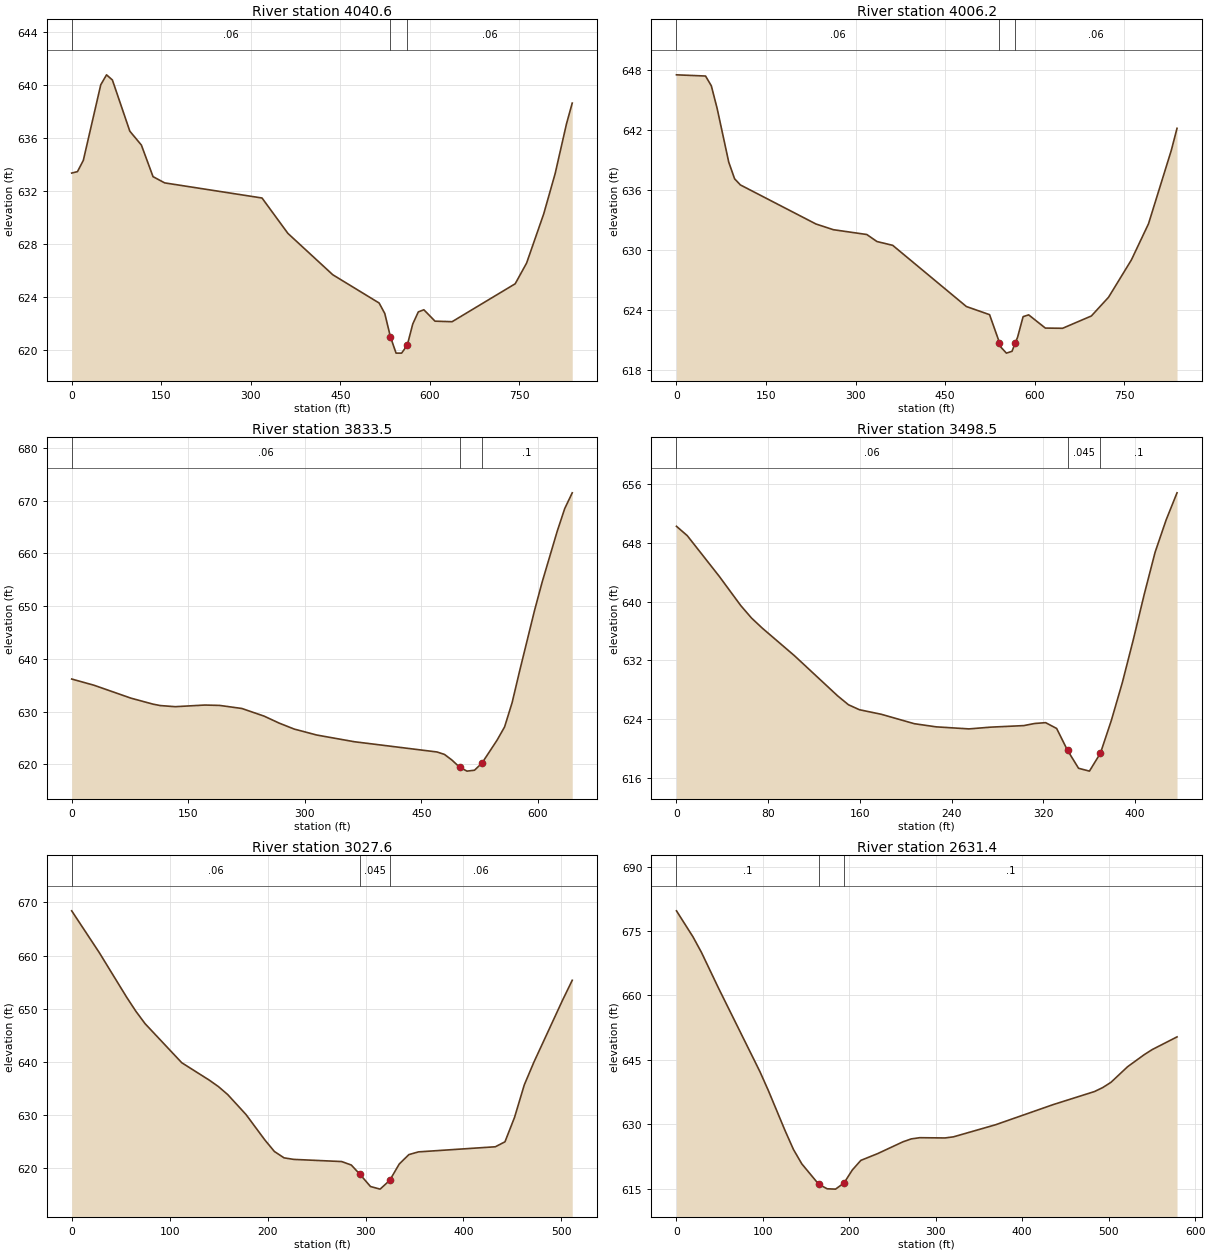
Type RM Length L Ch R = 1 ,4040.6  ,37.2,34.3,34.3
XS GIS Cut Line= 6
     1783303.473       570592.72       1783195.4      570256.783
      1783188.89       570067.98     1783135.504      570015.897
     1783084.723      569945.585     1783040.452      569819.283
#Sta/Elev= 30
       0  633.38     9.7  633.49    19.5  634.34    48.7  640.04    58.4  640.79
    68.2   640.4    97.4  636.54   116.8  635.49   136.3  633.11   155.8  632.64
   318.9   631.5   362.3  628.83   437.5  625.71   515.1  623.58   524.6  622.79
     534  621.04   543.5   619.8   552.8   619.8   562.2  620.39   571.5     622
   580.8  622.91   590.1  623.07   608.8  622.21   637.4  622.17   743.1  625.03
   762.2  626.59   790.9   630.3     810  633.33   829.1   637.1   838.7  638.66
#Mann= 3 , 0 , 0
       0     .06       0     534    .045       0   562.2     .06       0
Bank Sta=534,562.2
XS Rating Curve= 0 ,0
Exp/Cntr=0.3,0.1

Type RM Length L Ch R = 1 ,4006.2  ,160.3,172.7,192.2
XS GIS Cut Line= 6
     1783337.327      570579.699     1783229.254      570243.762
     1783222.744       570054.96     1783169.358      570002.876
     1783118.577      569932.564     1783074.306      569806.262
#Sta/Elev= 30
       0  647.48    48.7  647.36    58.4  646.38    68.2  644.11    87.6  638.76
    97.4   637.1   107.1  636.49   233.7  632.59   262.9  632.02   318.9  631.54
   335.9  630.84   362.3  630.46   485.8  624.35   524.6  623.54  541.18  620.75
   543.5   620.3   552.8   619.7   562.2  619.88  567.87  620.75   571.5  621.28
   580.8  623.34   590.1  623.52   618.1   622.2     647  622.18   695.2  623.41
     724  625.28   762.2     629   790.9  632.61   829.1  639.94   838.7  642.14
#Mann= 3 , 0 , 0
       0     .06       0  541.18    .045       0  567.87     .06       0
Bank Sta=541.18,567.87
XS Rating Curve= 0 ,0
Exp/Cntr=0.3,0.1

Type RM Length L Ch R = 1 ,3833.5  ,345.3,335,324.7
XS GIS Cut Line= 3
     1783336.025      570465.116      1783358.16      570228.137
     1783359.462      569821.887
#Sta/Elev= 30
       0  636.19    28.6  635.02    76.2  632.57   104.7  631.43   114.2  631.16
   133.3  630.95   171.4  631.26   190.4  631.19     219  630.61   247.7  629.16
     267  627.84   286.4  626.71   315.4  625.58   363.8  624.31   470.2  622.37
   479.8  621.91   489.5  620.83   499.2   619.5   508.8  618.74   518.5  618.91
   528.2  620.28   547.5   624.6   557.2  627.11   566.9  631.71   576.6  637.73
   595.9  649.26   605.6  654.57   624.9  664.16   634.6  668.48   644.3  671.47
#Mann= 3 , 0 , 0
       0     .06       0   499.2    .045       0   528.2      .1       0
Bank Sta=499.2,528.2
XS Rating Curve= 0 ,0
Exp/Cntr=0.3,0.1

Type RM Length L Ch R = 1 ,3498.5  ,470.2,470.9,471.3
XS GIS Cut Line= 3
     1783847.744      570152.616     1783760.504       570054.96
     1783640.712       569773.71
#Sta/Elev= 30
       0  650.26     9.4  648.99    37.4  643.43    56.1  639.46    65.5  637.76
    74.8   636.4   102.9  632.64   140.5  627.18     150  625.96   159.6  625.28
   178.7  624.66   207.4  623.38   226.5  622.95   255.1  622.67   274.2  622.91
   302.9  623.12   312.5  623.41     322  623.52   331.6  622.73   341.1  619.75
   350.7  617.31   360.2  616.92   369.8  619.37   379.3  623.82   388.9  628.98
   398.4  634.78     408     641   417.5  646.74   427.1  651.13   436.6  654.82
#Mann= 3 , 0 , 0
       0     .06       0   341.1    .045       0   369.8      .1       0
Bank Sta=341.1,369.8
XS Rating Curve= 0 ,0
Exp/Cntr=0.3,0.1

Type RM Length L Ch R = 1 ,3027.6  ,382.9,396.2,409
XS GIS Cut Line= 3
     1784183.681      570048.449     1784162.848      569862.251
     1784043.056       569561.47
#Sta/Elev= 30
       0  668.41    28.1  660.58    56.2  652.15    65.6  649.52    74.9  647.21
   112.4  639.86   140.5  636.59   149.9  635.37   159.3  633.88     178  630.13
   197.2  625.36     207  623.18   216.8  621.99   226.6   621.7   275.7  621.29
   285.5  620.64   294.4  618.88   305.1   616.6   314.9  616.11   324.7  617.75
   334.5  620.84   344.3   622.6   354.1  623.11   432.6  624.07   442.4     625
   452.2   629.6   462.1  635.68   471.9  639.95   501.3  651.65   511.1  655.36
#Mann= 3 , 0 , 0
       0     .06       0   294.4    .045       0   324.7     .06       0
Bank Sta=294.4,324.7
XS Rating Curve= 0 ,0
Exp/Cntr=0.3,0.1

Type RM Length L Ch R = 1 ,2631.4  ,422.2,429.8,438.1
XS GIS Cut Line= 4
     1784457.119       569998.97     1784468.837       569873.97
     1784515.712      569644.803     1784561.285       569429.96
#Sta/Elev= 30
       0   679.7    19.3  673.58      29  669.98    48.3  661.85    96.6  642.25
   106.2  637.92   125.6  628.56   135.3  624.17     145  620.81   164.5  616.08
   174.3  615.01     184  614.93   193.8  616.35   203.5   619.4   213.3  621.62
   232.8   623.2     262  625.94   271.7  626.62   281.5   626.9   310.7  626.84
   320.5   627.1     369   629.9   435.8   634.6   483.6  637.64   493.1  638.56
   502.7  639.79   521.8   643.4   540.9  646.19   550.4  647.41   579.1  650.36
#Mann= 3 , 0 , 0
       0      .1       0   164.5    .045       0   193.8      .1       0
Bank Sta=164.5,193.8
XS Rating Curve= 0 ,0
Exp/Cntr=0.3,0.1

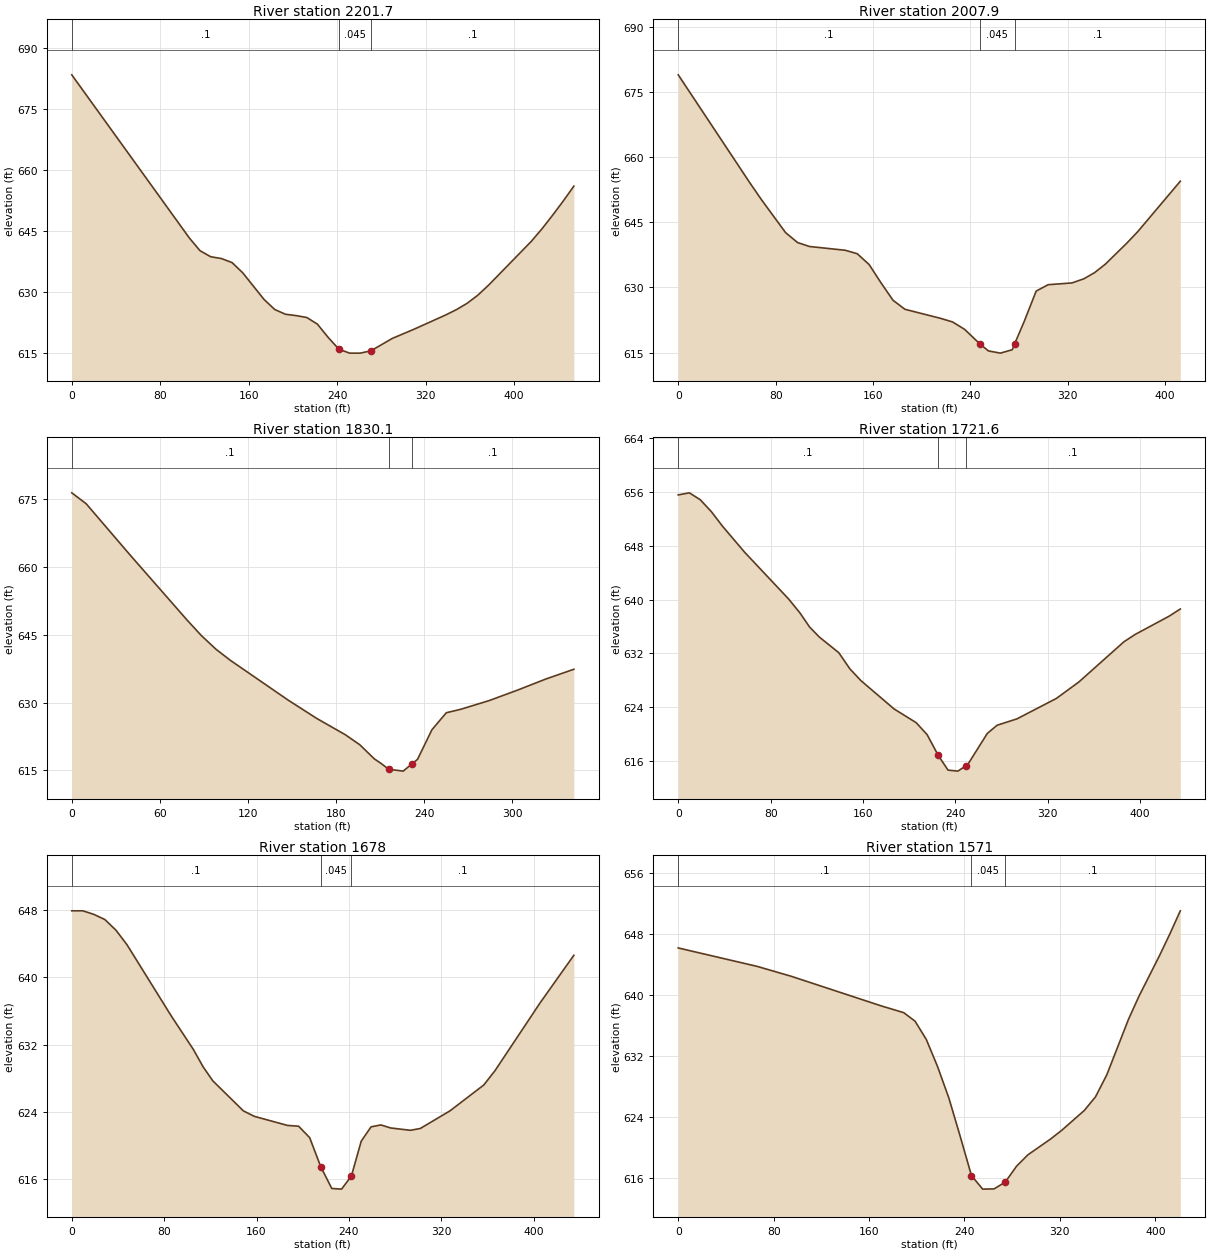
Type RM Length L Ch R = 1 ,2201.7  ,195.2,193.8,191.3
XS GIS Cut Line= 2
     1784806.077      570078.397      1784983.16      569660.428
#Sta/Elev= 30
       0   683.5   106.2  643.32   115.9  640.16   125.6  638.66   135.2  638.22
   144.9  637.22   154.5  634.72   173.8  628.14   183.5  625.65   193.2  624.48
   202.8  624.15   212.5  623.68   222.1  622.04   231.8  618.77   241.4   615.9
   251.1   614.9   260.8   614.9   270.4  615.46   289.8  618.53   309.1  620.75
     338   624.3   347.7  625.61   357.4  627.18     367  629.16   376.7  631.62
   415.3  642.41     425  645.51   434.6  648.85   444.3  652.38   453.9  656.06
#Mann= 3 , 0 , 0
       0      .1       0   241.4    .045       0   270.4      .1       0
Bank Sta=241.4,270.4
XS Rating Curve= 0 ,0
Exp/Cntr=0.3,0.1

Type RM Length L Ch R = 1 ,2007.9  ,176.4,177.8,178.8
XS GIS Cut Line= 3
     1784963.629      570129.178     1785104.254      569827.095
     1785151.129      569763.293
#Sta/Elev= 30
       0  678.89    58.8  654.07    68.6  650.09    88.2   642.6      98  640.33
   107.8  639.42   137.2  638.55     147  637.76   156.8  635.27   166.6  631.05
   176.4  627.06   186.2  624.98   215.6  622.89   225.4  622.06   235.2  620.37
  248.01  616.96   254.8  615.41   264.6   614.9   274.4  615.68  276.35  617.05
   284.2   622.2     294  629.16   303.8  630.63   323.4  631.04   333.2  631.99
     342  633.41   350.8  635.35   368.4  640.17   377.2  642.75   412.4  654.43
#Mann= 3 , 0 , 0
       0      .1       0  248.01    .045       0  276.35      .1       0
Bank Sta=248.01,276.35
XS Rating Curve= 0 ,0
Exp/Cntr=0.3,0.1

Type RM Length L Ch R = 1 ,1830.1  ,121.7,108.5,94.5
XS GIS Cut Line= 3
     1785112.067      570195.585     1785235.765       569961.21
     1785229.254      569884.387
#Sta/Elev= 24
       0  676.46     9.8  674.05    39.3  662.86    78.5  648.31    88.3  644.85
    98.2  641.84     108  639.38   147.2  630.61   166.9   626.5   186.5  622.87
   196.3  620.66   206.1  617.56  210.81  616.52   215.9  615.25   225.8  614.83
   231.8  616.43   235.6  617.44   245.4  623.99   255.2  627.76     265  628.52
   284.3  630.44   303.6  632.75   322.8   635.2   342.1  637.39
#Mann= 3 , 0 , 0
       0      .1       0   215.9    .045       0   231.8      .1       0
Bank Sta=215.9,231.8
XS Rating Curve= 0 ,0
Exp/Cntr=0.3,0.1

Type RM Length L Ch R = 1 ,1721.6  ,43,43.7,44.4
XS GIS Cut Line= 6
     1785402.431      570261.991     1785333.421      570182.564
     1785317.796      570152.616     1785307.379      570015.897
     1785286.546      569969.022     1785234.462      569875.272
#Sta/Elev= 30
       0  655.56     9.6  655.87    19.1  654.84    28.7  653.07    38.3  650.92
    57.4  647.06    95.6  640.09   105.2  638.07   113.7  635.94   122.1  634.45
     139  632.12   148.6  629.72   158.1  627.98   186.8  623.77     206  621.72
   215.5  619.94   225.1  616.86   233.6  614.67   242.1  614.52     249   615.3
   250.6  615.48   267.6  620.12   276.1  621.34   293.2  622.28   327.4  625.32
   346.9  627.77   385.9  633.74   395.7  634.84   424.9  637.53   434.7  638.61
#Mann= 3 , 0 , 0
       0      .1       0   225.1    .045       0     249      .1       0
Bank Sta=225.1,249
XS Rating Curve= 0 ,0
Exp/Cntr=0.3,0.1

Type RM Length L Ch R = 1 ,1678    ,110,107,102.8
XS GIS Cut Line= 6
     1785444.098      570259.387     1785375.087       570179.96
     1785359.462      570150.012     1785349.046      570013.293
     1785328.212      569966.418     1785276.129      569872.668
#Sta/Elev= 30
       0  647.92     9.6  647.92    19.1   647.5    28.7  646.88    38.3  645.61
    47.8  643.89    86.1  635.42   105.2  631.44   113.7  629.36   122.1  627.69
   148.6  624.11   158.1  623.46   186.8  622.38   196.4  622.29     206  620.92
   215.5  617.49   225.1  614.88   233.6   614.8   242.1  616.36   250.6   620.5
   259.1  622.21   267.6  622.44   276.1  622.08   293.2   621.8   301.8  622.02
   327.4  624.11   356.7  627.19   366.4  628.89   405.4  636.95   434.7  642.63
#Mann= 3 , 0 , 0
       0      .1       0   215.5    .045       0   242.1      .1       0
Bank Sta=215.5,242.1
XS Rating Curve= 0 ,0
Exp/Cntr=0.3,0.1

Type RM Length L Ch R = 1 ,1571    ,353.7,342.7,333
XS GIS Cut Line= 4
     1785608.525      570195.567     1785459.723      570064.074
      1785414.15      569900.012     1785415.452      569847.928
#Sta/Elev= 26
       0  646.14    66.2  643.72    94.6  642.43   170.2  638.54   189.1  637.65
   198.6  636.53     208  634.14   217.5  630.56     227  626.42   236.4  621.44
   245.9  616.27   255.3   614.5   264.8  614.53   274.2  615.42   283.7  617.51
   293.2     619   312.1  621.06   321.6  622.22   340.5  624.82   349.9  626.61
   359.4  629.51   377.5  636.76   386.2  639.76   403.6  645.15   412.3     648
     421  651.01
#Mann= 3 , 0 , 0
       0      .1       0   245.9    .045       0   274.2      .1       0
Bank Sta=245.9,274.2
XS Rating Curve= 0 ,0
Exp/Cntr=0.3,0.1