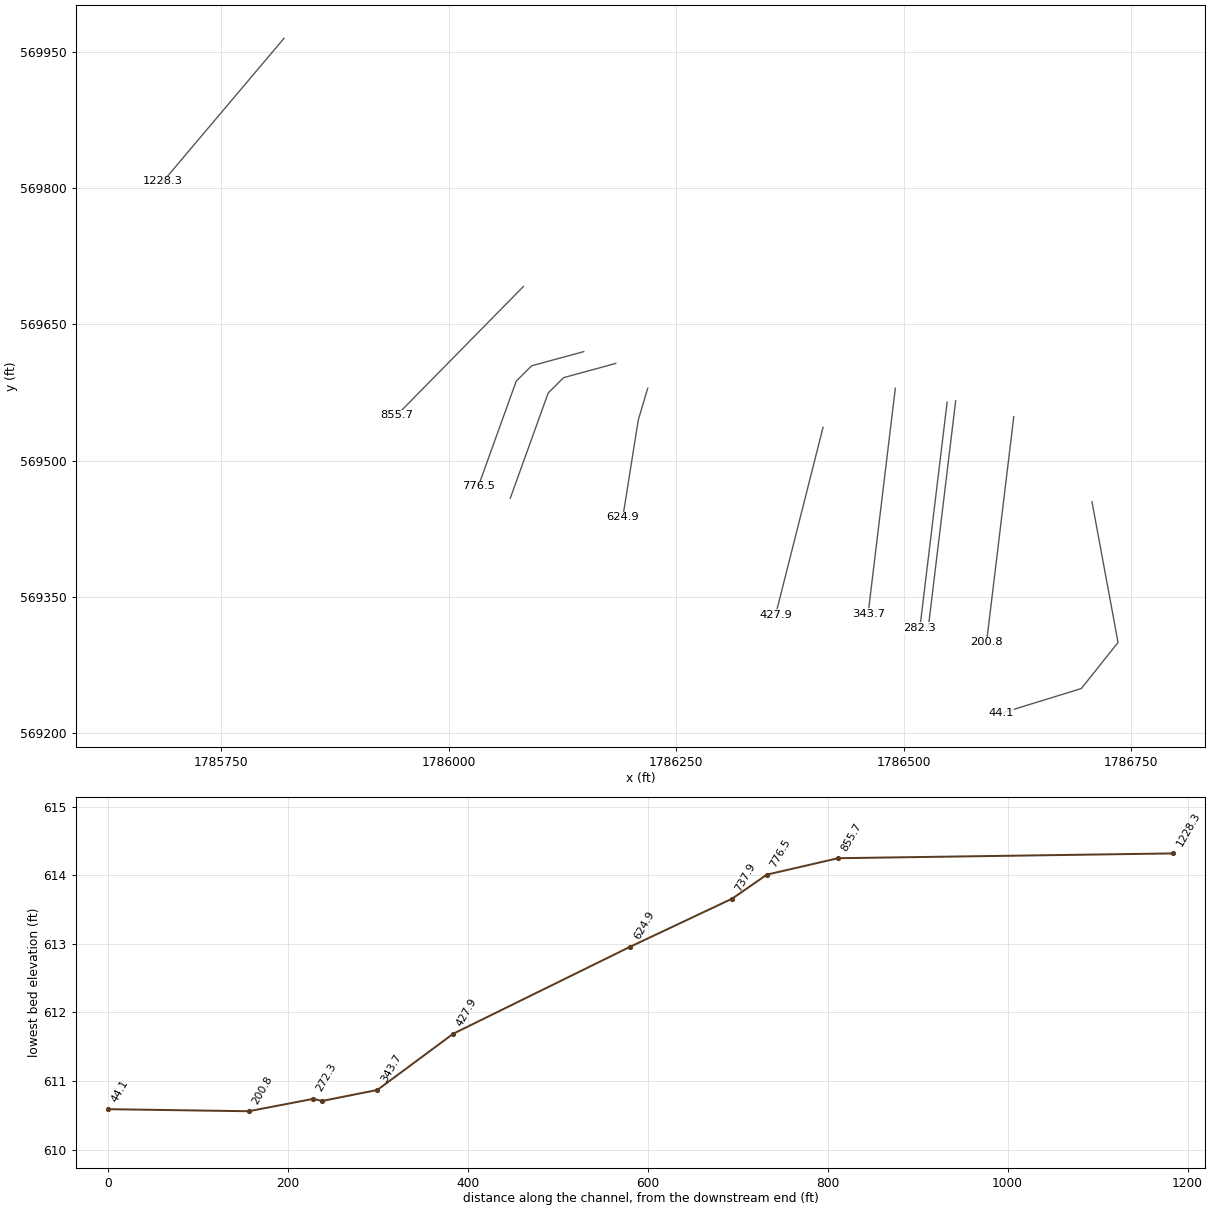
HEC-RAS study ALLENFK.prj: ALLENFK

--- ALLENFK.g01 (geometry) --- (continued)

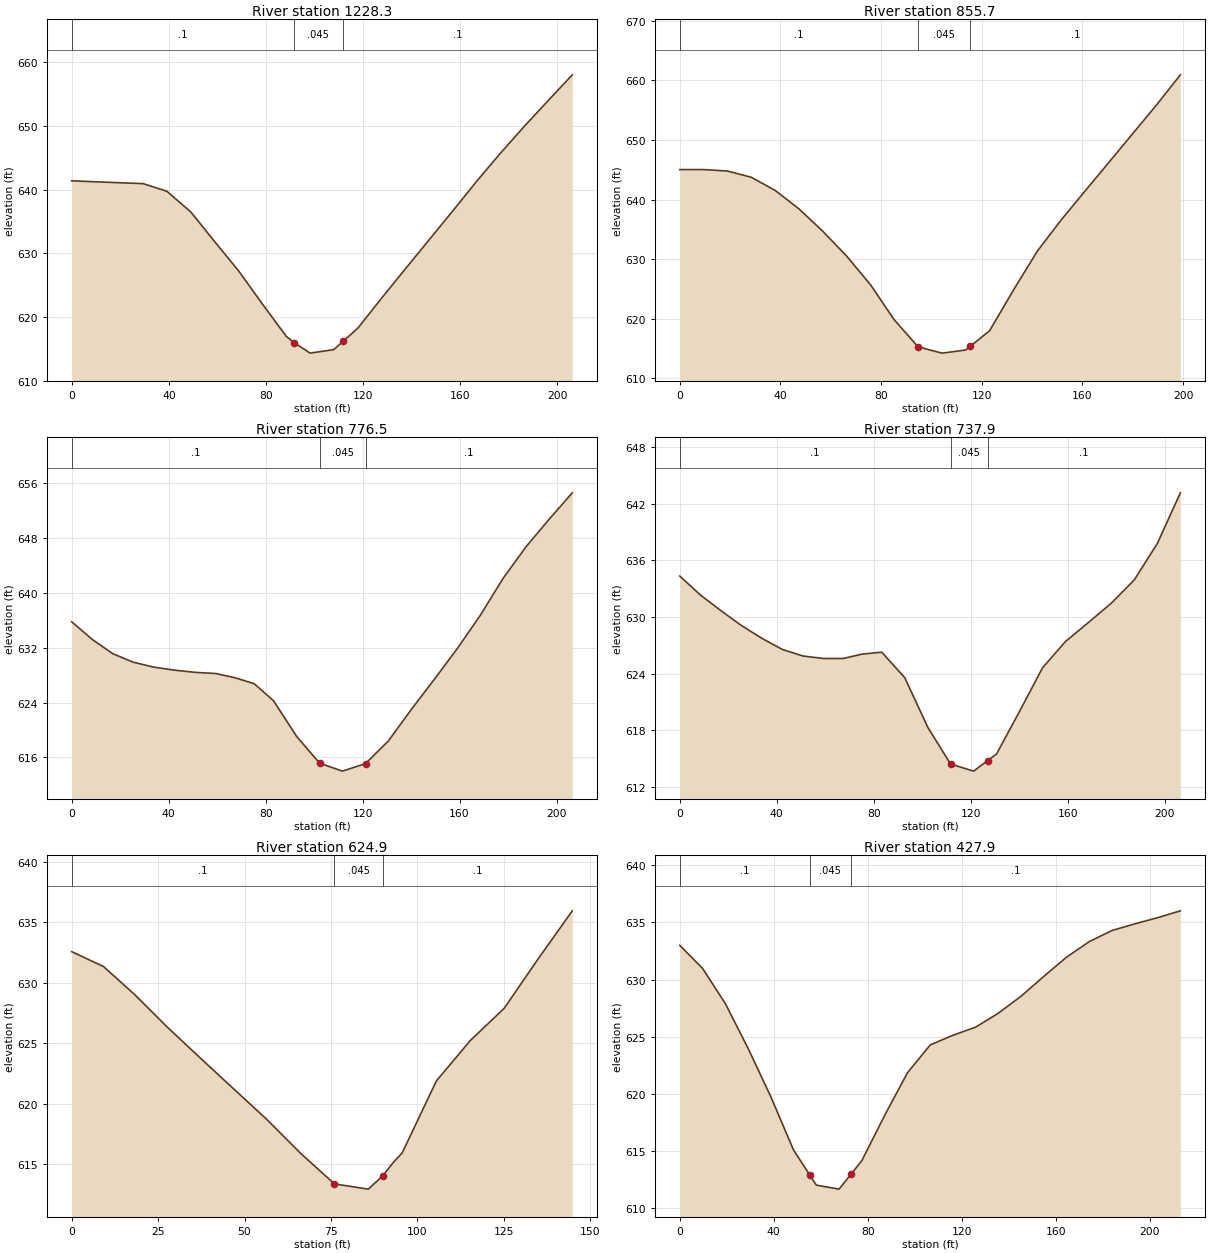
Type RM Length L Ch R = 1 ,1228.3  ,374.3,372.7,371
XS GIS Cut Line= 2
     1785819.098      569965.116     1785686.285      569807.564
#Sta/Elev= 25
       0   641.4     9.8  641.25    19.6   641.1    29.4  640.96    39.2  639.76
    49.1  636.48    58.9  631.83    68.7  627.26    78.5  622.05    88.3  616.98
   91.45  615.99    96.7   614.7    98.1  614.32   107.9  614.87   111.7  616.16
   117.8  618.24   127.6  622.96   137.4  627.57   147.2  632.14     157  636.72
   166.8  641.36   176.6  645.78   186.4  649.99   196.2  654.02   206.1  658.06
#Mann= 3 , 0 , 0
       0      .1       0   91.45    .045       0   111.7      .1       0
Bank Sta=91.45,111.7
XS Rating Curve= 0 ,0
Exp/Cntr=0.3,0.1

Type RM Length L Ch R = 1 ,855.7   ,69.1,79.2,89.2
XS GIS Cut Line= 2
     1786082.119      569691.678     1785942.796      569549.751
#Sta/Elev= 24
       0  645.05     9.5  645.05    18.9  644.81    28.4  643.76    37.9  641.55
    47.4  638.44    56.8  634.71    66.3  630.53    75.8  625.71    85.2  619.85
    94.7   615.3   100.4  614.67   104.2  614.25   113.6  614.77   115.4  615.38
   123.1  618.01   132.6  624.85   142.1  631.39   151.5  636.58     161  641.44
   170.5  646.26   179.9  651.05   189.4  655.88   198.9  660.95
#Mann= 3 , 0 , 0
       0      .1       0    94.7    .045       0   115.4      .1       0
Bank Sta=94.7,115.4
XS Rating Curve= 0 ,0
Exp/Cntr=0.3,0.1

Type RM Length L Ch R = 1 ,776.5   ,38.9,38.5,38.3
XS GIS Cut Line= 4
     1786148.525      569620.064     1786091.233      569604.439
     1786074.306      569587.512      1786032.64      569471.626
#Sta/Elev= 26
       0  635.79     8.5  633.22      17  631.13    25.4   629.9    33.9  629.18
    42.4  628.74    50.9  628.42    59.4  628.25    67.4  627.63    75.3  626.76
    83.3  624.26    92.8  619.07   102.3  615.16   103.7  614.99   111.7  614.01
   118.7  614.82   121.2  615.11   130.7  618.44   140.2  623.05   149.6  627.41
   159.1  631.91   168.6  636.76     178  642.15   187.5  646.78     197  650.77
   206.5  654.61
#Mann= 3 , 0 , 0
       0      .1       0   102.3    .045       0   121.2      .1       0
Bank Sta=102.3,121.2
XS Rating Curve= 0 ,0
Exp/Cntr=0.3,0.1

Type RM Length L Ch R = 1 ,737.9   ,108.9,113.1,117.2
XS GIS Cut Line= 4
     1786183.681      569607.043      1786126.39      569591.418
     1786109.462      569574.491     1786067.796      569458.605
#Sta/Elev= 26
       0  634.32     8.5  632.32      17  630.65    25.4  629.09    33.9  627.72
    42.4  626.54    50.9  625.85    59.4  625.59    67.4  625.59    75.3  626.06
    83.3  626.26    92.8  623.56   102.3   618.3   111.7  614.41     112  614.39
   121.2  613.66     127  614.78   130.7  615.49   140.2  620.01   149.6  624.59
   159.1  627.39   168.6  629.41     178  631.45   187.5  633.92     197  637.78
   206.5  643.14
#Mann= 3 , 0 , 0
       0      .1       0   111.7    .045       0     127      .1       0
Bank Sta=111.7,127
XS Rating Curve= 0 ,0
Exp/Cntr=0.3,0.1

Type RM Length L Ch R = 1 ,624.9   ,198.9,196.9,194.9
XS GIS Cut Line= 3
     1786218.837      569579.699     1786208.421      569544.543
     1786191.494      569437.772
#Sta/Elev= 19
       0  632.57     9.2  631.34    18.3     629    27.5  626.38    36.7  623.92
    46.5  621.33    56.3  618.75    66.2  615.92      76  613.39    78.1   613.3
    85.8  612.96   89.99  614.06    93.1  615.19    95.6  615.95   105.5   621.9
   115.3  625.23   125.1  627.89   134.9  631.96   144.8  635.94
#Mann= 3 , 0 , 0
       0      .1       0      76    .045       0   89.99      .1       0
Bank Sta=76,89.99
XS Rating Curve= 0 ,0
Exp/Cntr=0.3,0.1

Type RM Length L Ch R = 1 ,427.9   ,81.3,84.3,87.3
XS GIS Cut Line= 2
     1786411.546       569536.73     1786359.393      569330.116
#Sta/Elev= 26
       0  632.99     9.7  630.98    19.4   627.9    29.1  623.98    38.7  619.79
    48.4  615.12   55.36  612.91    57.8  612.14    58.1  612.04    67.8  611.69
    72.8  612.97    77.5  614.18    87.2  618.13    96.9  621.85   106.6  624.29
   116.2  625.13   125.9  625.84   135.6  627.06   145.3  628.55     155  630.29
   164.7  631.97   174.4  633.33     184  634.29   193.7  634.87   203.4  635.41
   213.1  636.01
#Mann= 3 , 0 , 0
       0      .1       0   55.36    .045       0    72.8      .1       0
Bank Sta=55.36,72.8
XS Rating Curve= 0 ,0
Exp/Cntr=0.3,0.1

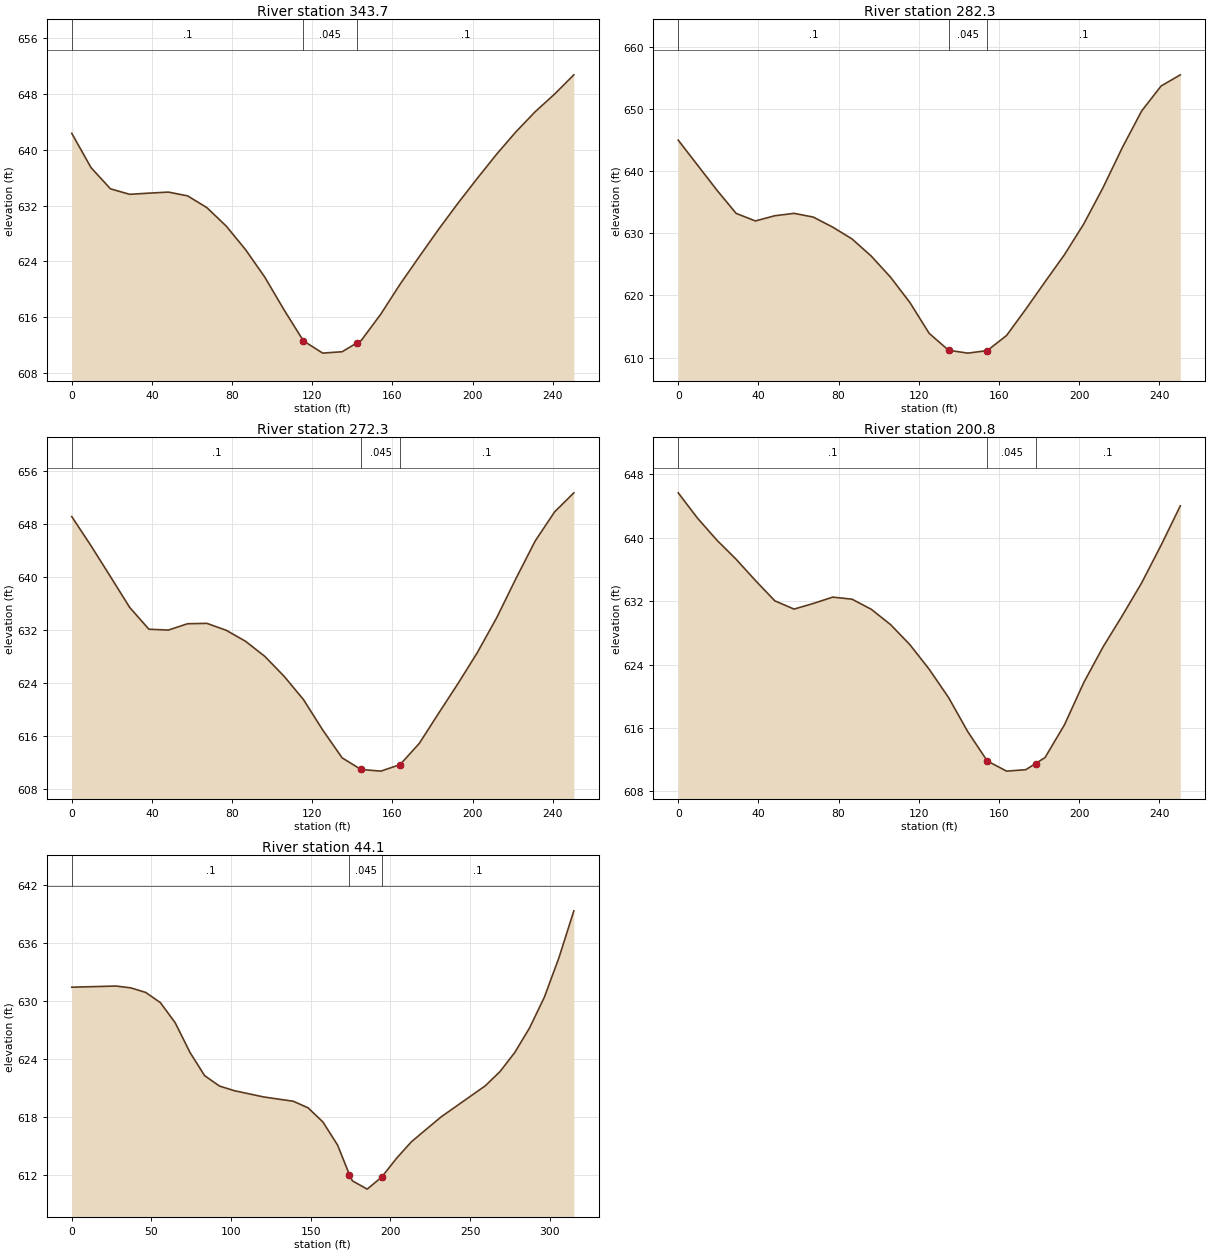
Type RM Length L Ch R = 1 ,343.7   ,61,61.4,61.8
XS GIS Cut Line= 2
     1786490.973      569579.699     1786461.025      569331.001
#Sta/Elev= 29
       0  642.36     9.6  637.45    19.3  634.41    28.9  633.62    38.5  633.79
    48.2  633.94    57.8   633.4    67.4  631.72    77.1  629.06    86.7   625.7
    96.3  621.76     106  617.03   115.6  612.62   125.2  610.87   127.5  610.92
   134.9  611.07   142.5  612.37   144.5  612.71   154.2  616.46   163.8  620.74
   173.4   624.7     183   628.6   192.7  632.35   202.3   635.9     212  639.38
   221.6  642.57   231.2  645.45   240.9  647.98   250.5  650.74
#Mann= 3 , 0 , 0
       0      .1       0   115.6    .045       0   142.5      .1       0
Bank Sta=115.6,142.5
XS Rating Curve= 0 ,0
Exp/Cntr=0.3,0.1

Type RM Length L Ch R = 1 ,282.3   ,10,10,10
XS GIS Cut Line= 2
     1786547.917      569564.421     1786517.969      569315.723
#Sta/Elev= 29
       0  644.95     9.6  640.95    19.3  636.91    28.9  633.17    38.5  631.96
    48.2   632.8    57.8  633.18    67.4  632.58    77.1  630.96    86.7  629.07
    96.3  626.31     106  622.89   115.6  618.84   125.2  613.89   134.9  611.17
   137.8  611.03   144.5  610.71   152.8  611.06   154.2  611.12   163.8  613.54
   173.4  617.77     183  622.17   192.7  626.54   202.3  631.46     212  637.35
   221.6  643.77   231.2  649.63   240.9  653.65   250.5  655.45
#Mann= 3 , 0 , 0
       0      .1       0   134.9    .045       0   154.2      .1       0
Bank Sta=134.9,154.2
XS Rating Curve= 0 ,0
Exp/Cntr=0.3,0.1

Type RM Length L Ch R = 1 ,272.3   ,71.5,71.5,71.6
XS GIS Cut Line= 2
     1786557.292       569565.81     1786527.344      569317.112
#Sta/Elev= 28
       0  649.08     9.6  644.69    19.3  640.04    28.9   635.4    38.5  632.11
    48.2  631.99    57.8  632.94    67.4     633    77.1  631.95    86.7   630.3
    96.3  628.03     106  625.01   115.6  621.52   125.2  616.94   134.9  612.74
   144.3  610.99   154.2  610.74   159.3  611.26   163.8  611.72   173.4  614.92
     183  619.44   192.7  623.93   202.3  628.57     212  633.84   221.6  639.74
   231.2   645.4   240.9  649.79   250.5  652.66
#Mann= 3 , 0 , 0
       0      .1       0   144.3    .045       0   163.8      .1       0
Bank Sta=144.3,163.8
XS Rating Curve= 0 ,0
Exp/Cntr=0.3,0.1

Type RM Length L Ch R = 1 ,200.8   ,169.3,156.7,143.3
XS GIS Cut Line= 2
     1786621.181      569548.449     1786591.233      569299.751
#Sta/Elev= 29
       0  645.65     9.6  642.46    19.3  639.68    28.9  637.27    38.5   634.6
    48.2  632.03    57.8  630.99    67.4   631.7    77.1   632.5    86.7  632.24
    96.3  630.97     106  629.02   115.6   626.5   125.2  623.41   134.9  619.83
   144.5  615.52   154.2  611.84   163.3  610.63   163.8  610.56   173.4  610.74
   178.3  611.52     183  612.27   192.7   616.4   202.3  621.71     212  626.24
   221.6  630.18   231.2  634.29   240.9  639.04   250.5  644.01
#Mann= 3 , 0 , 0
       0      .1       0   154.2    .045       0   178.3      .1       0
Bank Sta=154.2,178.3
XS Rating Curve= 0 ,0
Exp/Cntr=0.3,0.1

Type RM Length L Ch R = 1 ,44.1    ,48.5,44.1,39.8
XS GIS Cut Line= 4
     1786707.119      569454.699     1786735.765      569299.751
       1786695.4       569248.97     1786606.858      569221.626
#Sta/Elev= 29
       0  631.45    27.8  631.57    37.1  631.38    46.4  630.91    55.6  629.86
    64.9  627.78    74.2  624.71    83.4  622.31    92.7  621.24     102  620.76
   120.5  620.11     139  619.67   148.3  618.99   157.6  617.53   166.8  615.15
  174.22   612.1   176.1  611.45   185.4  610.59   194.5  611.83   203.9  613.79
   213.2  615.49   231.7  618.04   259.5  621.26   268.8  622.74     278   624.7
   287.3  627.24   296.6  630.42   305.8  634.52   315.1  639.34
#Mann= 3 , 0 , 0
       0      .1       0  174.22    .045       0   194.5      .1       0
Bank Sta=174.22,194.5
XS Rating Curve= 0 ,0
Exp/Cntr=0.3,0.1

Chan Stop Cuts=-1
Use User Specified Reach Order=0
Composite Channel Slope=5